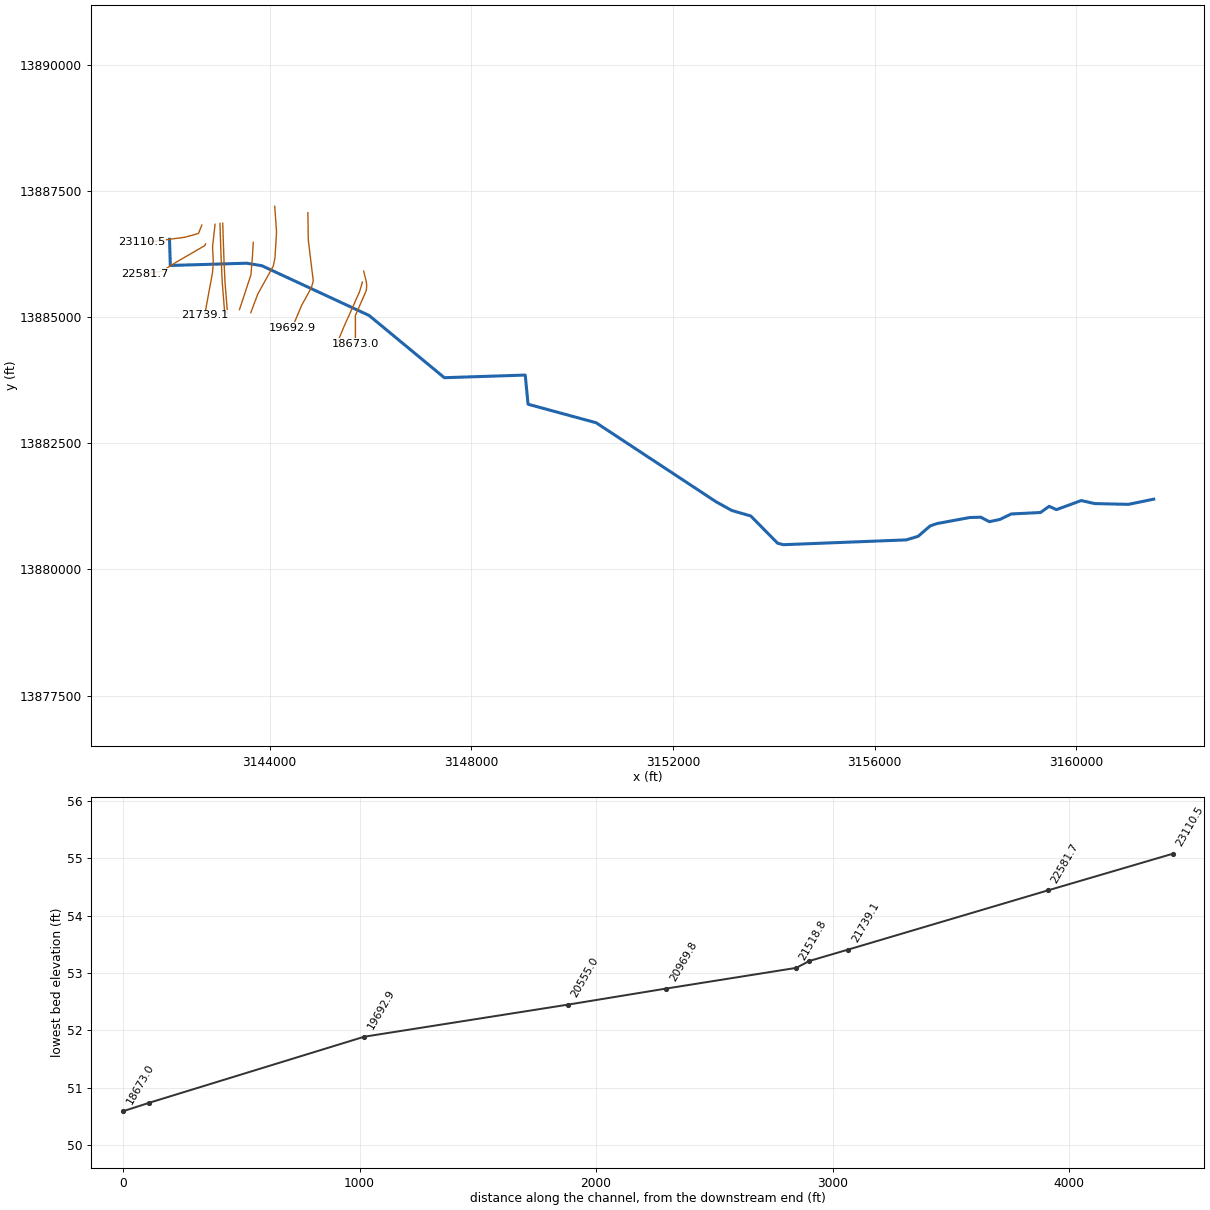
--- P125-00-00.PRJ (project) ---

Proj Title=P125-00-00
Current Plan=p02
Default Exp/Contr=.3,.1
English Units
Geom File=g01
Flow File=f01
Flow File=f02
Plan File=p01
Plan File=p02
Y Axis Title=Elevation
X Axis Title(PF)=Main Channel Distance
X Axis Title(XS)=Station
BEGIN DESCRIPTION:
Greens Bayou Watershed
Tributary 14.27 to Greens Bayou
HCFCD Unit P125-00-00
Flood Hazard Model
10, 2, 1, 0.2% Event
Filename P125-00-00.prj
Prepared by:  Watershed Concepts  Date:
Reviewed by:                      Date:
STATUS FINAL
END DESCRIPTION:
DSS Export Rating Curves= 0
DSS Export Rating Curve Sorted= 0
DSS Export Volume Flow Curves= 0
DXF OffsetX= 0
DXF OffsetY= 0
DXF ScaleX= 1
DXF ScaleY= 10

--- P125-00-00.p02 (plan) ---

Plan Title=Floodway
Version=Version 3.0.1  Mar 2001
Short Identifier=Floodway0607
Geom File=g01
Flow File=f02
Subcritical Flow
K Sum by GR= 0
Std Step Tol= 0.01
Critical Tol= 0.01
Num of Std Step Trials= 20
Max Error Tol= 0.3
Flow Tol Ratio= 0.001
Split Flow NTrial= 30
Split Flow Tol= 0.02
Split Flow Ratio= 0.02
Log Output Level= 0
Friction Slope Method= 1
Unsteady Friction Slope Method= 2
Parabolic Critical Depth
Global Vel Dist= 0 , 0 , 0
Global Log Level= 0
CheckData=True
Encroach Param=-1 ,0,0, 2
Encroach River=P125-00-00
Encroach Reach=Reach - 1
Encroach Node=23110.5
       1    4960    5030
Encroach Node=22581.7
       1  4972.4  5032.8
Encroach Node=21739.1
       1  4976.8  5032.8
Encroach Node=21573.8
       1  4976.8  5032.8
Encroach Node=21546.3
       1  4976.8  5032.8
Encroach Node=21518.8
       1  4976.8  5032.8
Encroach Node=20969.8
       1    4966  5017.2
Encroach Node=20555.0
       1  4962.5    5067
Encroach Node=19692.9
       1    4725 5020.15
Encroach Node=18785.3
       1  4951.9  5028.2
Encroach Node=18673.0
       1  4951.9  5028.2
Encroach Node=18645.5
       1  4951.9  5028.2
Encroach Node=18618.0
       1  4951.9  5028.2
Encroach Node=18091.3
       1    4975    5024
Encroach Node=17722.0
       1  4978.3    5024
Encroach Node=17185.9
       1    4954    5093
Encroach Node=17016.6
       1 4962.24 5088.59
Encroach Node=16954.1
       1 4962.24 5088.59
Encroach Node=16891.6
       1 4962.24 5088.59
Encroach Node=16465.1
       1    4975    5100
Encroach Node=15810.2
       1    4950    5060
Encroach Node=14969.6
       1    4945    5110
Encroach Node=14871.3
       1    4950    5120
Encroach Node=14523.3
       1    4950    5050
Encroach Node=14435.4
       1    4950    5050
Encroach Node=14377.4
       1    4950    5050
Encroach Node=14319.4
       1    4950    5050
Encroach Node=13788.1
       1    4670    5200
Encroach Node=13257.5
       1    4670    5200
Encroach Node=12856.8
       1    4965    5031
Encroach Node=12832.8
       1    4965    5031
Encroach Node=12808.8
       1    4965    5031
Encroach Node=12170.0
       1  4731.5    5300
Encroach Node=11742.5
       1    4700    5300
Encroach Node=11077.9
       1    4800    5300
Encroach Node=10567.3
       1    4900    5200
Encroach Node=10198.0
       1    4900    5150
Encroach Node=10041.4
       1    4800    5200
Encroach Node=10008.2
       1    4800    5200
Encroach Node=9975.0
       1    4800    5200
Encroach Node=9314.4
       1  4953.5  5070.3
Encroach Node=8816.8
       1  4965.1  5050.4
Encroach Node=8480.7
       1  4925.6  5040.1
Encroach Node=7745.2
       1  4950.1  5040.1
Encroach Node=6848.7
       1 4955.25 5044.75
Encroach Node=5685.9
       1  4954.9  5035.3
Encroach Node=4853.9
       1  4963.8  5036.2
Encroach Node=3645.2
       1  4973.6  5061.7
Encroach Node=2679.4
       1  4977.8  5044.3
Encroach Node=1773.1
       1  4932.2  5041.5
Encroach Node=770.1
       1  4964.2  5044.3
Encroach Reach=P125-00-00_0008
Encroach Node=23110.5
       1    4960    5030
Encroach Node=22581.7
       1  4972.4  5032.8
Encroach Node=21739.1
       1  4976.8  5032.8
Encroach Node=21573.8
       1  4976.8  5032.8
Encroach Node=21546.3
       1  4976.8  5032.8
Encroach Node=21518.8
       1  4976.8  5032.8
Encroach Node=20969.8
       1    4966  5017.2
Encroach Node=20555.0
       1  4962.5    5067
Encroach Node=19692.9
       1    4725 5020.15
Encroach Node=18785.3
       1  4951.9  5028.2
Encroach Node=18673.0
       1  4951.9  5028.2
Encroach Node=18645.5
       1  4951.9  5028.2
Encroach Node=18618.0
       1  4951.9  5028.2
Encroach Node=18091.3
       1    4975    5024
Encroach Node=17722.0
       1  4978.3    5024
Encroach Node=17185.9
       1    4954    5093
Encroach Node=17016.6
       1 4962.24 5088.59
Encroach Node=16954.1
       1 4962.24 5088.59
Encroach Node=16891.6
       1 4962.24 5088.59
Encroach Node=16465.1
       1    4975    5100
Encroach Node=15810.2
       1    4950    5060
Encroach Node=14969.6
       1    4945    5110
Encroach Node=14871.3
       1    4950    5120
Encroach Node=14523.3
       1    4950    5050
Encroach Node=14435.4
       1    4950    5050
Encroach Node=14377.4
       1    4950    5050
Encroach Node=14319.4
       1    4950    5050
Encroach Node=13788.1
       1    4670    5200
Encroach Node=13257.5
       1    4670    5200
Encroach Node=12856.8
       1    4965    5031
Encroach Node=12832.8
       1    4965    5031
Encroach Node=12808.8
       1    4965    5031
Encroach Node=12170.0
       1  4731.5    5300
Encroach Node=11742.5
       1    4700    5300
Encroach Node=11077.9
       1    4800    5300
Encroach Node=10567.3
       1    4900    5200
Encroach Node=10198.0
       1    4900    5150
Encroach Node=10041.4
       1    4800    5200
Encroach Node=10008.2
       1    4800    5200
Encroach Node=9975.0
       1    4800    5200
Encroach Node=9314.4
       1  4953.5  5070.3
Encroach Node=8816.8
       1  4965.1  5050.4
Encroach Node=8480.7
       1  4925.6  5040.1
Encroach Node=7745.2
       1  4950.1  5040.1
Encroach Node=6848.7
       1 4955.25 5044.75
Encroach Node=5685.9
       1  4954.9  5035.3
Encroach Node=4853.9
       1  4963.8  5036.2
Encroach Node=3645.2
       1  4973.6  5061.7
Encroach Node=2679.4
       1  4977.8  5044.3
Encroach Node=1773.1
       1  4932.2  5041.5
Encroach Node=770.1
       1  4964.2  5044.3
Computation Interval=1HOUR
Output Interval=1HOUR
Run HTab= 0
Run UNet= 0
Run PostProcess= 0
UNET Theta= 1
UNET ZTol= 0.02
UNET ZSATol= 0.1
UNET MxIter= 20
UNET MaxInSteps= 20
UNET DtIC= 0
UNET DtMin= 0
UNET MaxCRTS= 20
UNET WFStab= 2
UNET SFStab= 1
UNET WFX= 1
UNET SFX= 1
UNET Convert EG Bridges=-1
UNET Use Existing IB Tables=-1
Instantaneous Interval=1HOUR
Write IC File= 0
Write Velocity= 0
Write Detailed= 0

--- P125-00-00.p01 (plan) ---

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Plan Title=FEMA Effective June 2007
Short Identifier=FEMAeff0607
Geom File=g01
Flow File=f01
Encroach Param=-1 ,0,0, 0

--- P125-00-00.f02 (steady flow) ---

Flow Title= Floodway
Number of Profiles= 2
Profile Names=1PCT_100yr, 1PCTFloodway_100yrFW
River Rch & RM=P125-00-00,P125-00-00_0008,23110.5
     420     420
River Rch & RM=P125-00-00,P125-00-00_0008,22581.7
     476     476
River Rch & RM=P125-00-00,P125-00-00_0008,21573.8
     534     534
River Rch & RM=P125-00-00,P125-00-00_0008,20969.8
     568     568
River Rch & RM=P125-00-00,P125-00-00_0008,20555
     646     646
River Rch & RM=P125-00-00,P125-00-00_0008,19692.9
     754     754
River Rch & RM=P125-00-00,P125-00-00_0008,18785.3
     769     769
River Rch & RM=P125-00-00,P125-00-00_0008,18673
     794     794
River Rch & RM=P125-00-00,P125-00-00_0008,17722
     828     828
River Rch & RM=P125-00-00,P125-00-00_0008,16465.1
     847     847
River Rch & RM=P125-00-00,P125-00-00_0008,15810.2
     874     874
River Rch & RM=P125-00-00,P125-00-00_0008,14871.3
     887     887
River Rch & RM=P125-00-00,P125-00-00_0008,14435.4
     925     925
River Rch & RM=P125-00-00,P125-00-00_0008,14377.4
    1123    1123
River Rch & RM=P125-00-00,P125-00-00_0008,13788.1
    1362    1362
River Rch & RM=P125-00-00,P125-00-00_0008,13257.5
    1577    1577
River Rch & RM=P125-00-00,P125-00-00_0008,12856.8
    1621    1621
River Rch & RM=P125-00-00,P125-00-00_0008,12170
    1649    1649
River Rch & RM=P125-00-00,P125-00-00_0008,11742.5
    1693    1693
River Rch & RM=P125-00-00,P125-00-00_0008,11077.9
    1754    1754
River Rch & RM=P125-00-00,P125-00-00_0008,10198
    1818    1818
River Rch & RM=P125-00-00,P125-00-00_0008,9314.4
    1880    1880
River Rch & RM=P125-00-00,P125-00-00_0008,8480.7
    1936    1936
River Rch & RM=P125-00-00,P125-00-00_0008,7745.2
    2007    2007
River Rch & RM=P125-00-00,P125-00-00_0008,6848.7
    2103    2103
River Rch & RM=P125-00-00,P125-00-00_0008,5685.9
    2175    2175
River Rch & RM=P125-00-00,P125-00-00_0008,4853.9
    2283    2283
River Rch & RM=P125-00-00,P125-00-00_0008,3645.2
    2374    2374
River Rch & RM=P125-00-00,P125-00-00_0008,2679.4
    2462    2462
River Rch & RM=P125-00-00,P125-00-00_0008,1773.1
    2563    2563
Boundary for River Rch & Prof#=P125-00-00,P125-00-00_0008, 1
Up Type= 0
Dn Type= 3
Dn Slope= 0.00460
Boundary for River Rch & Prof#=P125-00-00,P125-00-00_0008, 2
Up Type= 0
Dn Type= 1
Dn Known WS=24.41

--- P125-00-00.f01 (steady flow) ---

Flow Title= FEMA Effective June 2007
Number of Profiles= 4
Profile Names=10PCT_10yr, 2PCT_50yr, 1PCT_100yr, 0.2PCT_500yr
River Rch & RM=P125-00-00,P125-00-00_0008,23110.5
     238     358     420     602
River Rch & RM=P125-00-00,P125-00-00_0008,22581.7
     270     406     476     279
River Rch & RM=P125-00-00,P125-00-00_0008,21573.8
     303     456     534     765
River Rch & RM=P125-00-00,P125-00-00_0008,20969.8
     322     485     568     813
River Rch & RM=P125-00-00,P125-00-00_0008,20555
     367     551     646     925
River Rch & RM=P125-00-00,P125-00-00_0008,19692.9
     428     644     754    1080
River Rch & RM=P125-00-00,P125-00-00_0008,18785.3
     436     656     769    1101
River Rch & RM=P125-00-00,P125-00-00_0008,18673
     451     677     794    1137
River Rch & RM=P125-00-00,P125-00-00_0008,17722
     470     707     828    1186
River Rch & RM=P125-00-00,P125-00-00_0008,16465.1
     481     723     847    1213
River Rch & RM=P125-00-00,P125-00-00_0008,15810.2
     496     746     874    1252
River Rch & RM=P125-00-00,P125-00-00_0008,14871.3
     503     757     887    1270
River Rch & RM=P125-00-00,P125-00-00_0008,14435.4
     518     787     925    1328
River Rch & RM=P125-00-00,P125-00-00_0008,14377.4
     588     944    1123    1627
River Rch & RM=P125-00-00,P125-00-00_0008,13788.1
     668    1132    1362    1994
River Rch & RM=P125-00-00,P125-00-00_0008,13257.5
     735    1298    1577    2324
River Rch & RM=P125-00-00,P125-00-00_0008,12856.8
     760    1334    1621    2391
River Rch & RM=P125-00-00,P125-00-00_0008,12170
     775    1358    1649    2433
River Rch & RM=P125-00-00,P125-00-00_0008,11742.5
     801    1395    1693    2500
River Rch & RM=P125-00-00,P125-00-00_0008,11077.9
     835    1445    1754    2592
River Rch & RM=P125-00-00,P125-00-00_0008,10198
     872    1498    1818    2688
River Rch & RM=P125-00-00,P125-00-00_0008,9314.4
     907    1549    1880    2782
River Rch & RM=P125-00-00,P125-00-00_0008,8480.7
     940    1596    1936    2867
River Rch & RM=P125-00-00,P125-00-00_0008,7745.2
     981    1655    2007    2975
River Rch & RM=P125-00-00,P125-00-00_0008,6848.7
    1038    1735    2103    3120
River Rch & RM=P125-00-00,P125-00-00_0008,5685.9
    1080    1794    2175    3229
River Rch & RM=P125-00-00,P125-00-00_0008,4853.9
    1145    1884    2283    3393
River Rch & RM=P125-00-00,P125-00-00_0008,3645.2
    1199    1959    2374    3530
River Rch & RM=P125-00-00,P125-00-00_0008,2679.4
    1253    2033    2462    3664
River Rch & RM=P125-00-00,P125-00-00_0008,1773.1
    1315    2117    2563    3818
Boundary for River Rch & Prof#=P125-00-00,P125-00-00_0008, 1
Up Type= 0
Dn Type= 3
Dn Slope= 0.00460
Boundary for River Rch & Prof#=P125-00-00,P125-00-00_0008, 2
Up Type= 0
Dn Type= 3
Dn Slope= 0.00460
Boundary for River Rch & Prof#=P125-00-00,P125-00-00_0008, 3
Up Type= 0
Dn Type= 3
Dn Slope= 0.00460
Boundary for River Rch & Prof#=P125-00-00,P125-00-00_0008, 4
Up Type= 0
Dn Type= 3
Dn Slope= 0.00460

--- P125-00-00.g01 (geometry) ---

Geom Title=P125-00-00 June 2007
Version=Version 3.0.1  Mar 2001

River Reach=P125-00-00      ,P125-00-00_0008
Reach XY= 30
      3142016.16     13886545.92        3142032.       13886027.
        3143545.       13886072.       3143847.5       13886022.
       3145973.5       13885036.       3147465.5       13883802.
      3149069.75       13883854.       3149125.5       13883276.
        3150475.       13882909.        3152855.       13881341.
       3153168.5       13881168.        3153541.       13881061.
        3154075.       13880519.      3154189.75       13880491.
        3156624.       13880586.      3156860.25       13880657.
      3157096.75       13880862.       3157225.5       13880908.
       3157884.5       13881030.       3158101.4     13881035.95
      3158273.18     13880947.38      3158477.16     13880990.32
      3158707.99     13881100.37      3159286.72     13881128.99
      3159457.94     13881251.92      3159602.83     13881186.07
      3160094.56     13881366.08       3160362.5       13881306.
      3161032.25       13881291.       3161532.5       13881394.

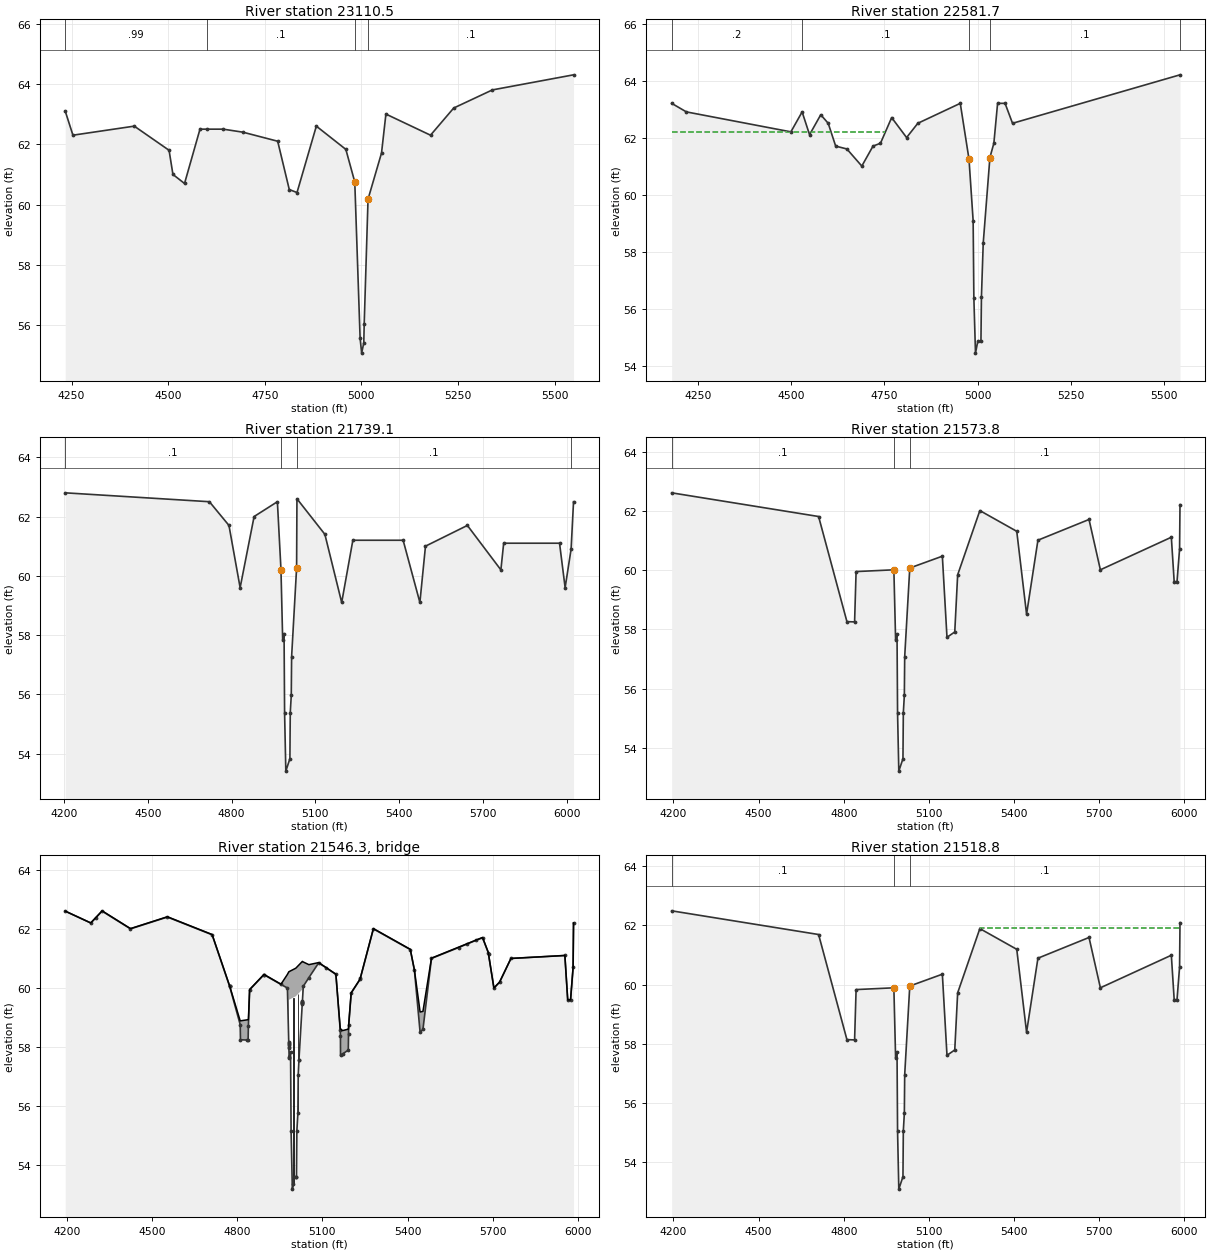
Type RM Length L Ch R = 1 ,23110.5 ,489.3,528.8,575.1
BEGIN DESCRIPTION:
Cross Section 23110.5
END DESCRIPTION:
XS GIS Cut Line= 5
      3142657.29     13886828.23      3142590.65     13886662.46
      3142320.05     13886586.61      3141838.95     13886522.13
       3141470.6     13886487.23
#Sta/Elev= 27
  4233.7    63.1  4253.7    62.3  4412.4    62.6  4502.4    61.8  4512.4      61
  4542.4    60.7  4582.4    62.5  4599.7    62.5  4642.4    62.5  4693.4    62.4
  4783.4    62.1  4813.4    60.5  4833.4    60.4  4883.4    62.6 4959.75   61.83
 4982.85   60.75 4996.65   55.57 5000.65   55.08 5006.15   55.42 5007.25   56.05
 5017.15   60.18 5052.05   61.71  5063.4      63  5178.8    62.3  5238.8    63.2
  5338.8    63.8  5548.8    64.3
#Mann= 4 , 1 , 0
  4233.7     .99       0  4599.7      .1       0 4982.85     .04       0
 5017.15      .1       0
#XS Ineff= 2 , 0
       0  4878.9    62.4  5063.4       0      63
Permanent Ineff=
       F       F
Bank Sta=4982.85,5017.15
XS Rating Curve= 0
Exp/Cntr=.3,.1

Type RM Length L Ch R = 1 ,22581.7 ,791.1,842.6,872.7
BEGIN DESCRIPTION:
Cross Section 22581.7-Interpolated
END DESCRIPTION:
XS GIS Cut Line= 5
      3142731.31     13886454.87      3142713.58     13886419.69
      3142147.97     13886091.87      3141869.85     13885916.21
      3141534.27     13885863.08
#Sta/Elev= 30
  4180.2    63.2  4219.6    62.9  4499.6    62.2  4529.7    62.9  4549.6    62.1
  4579.6    62.8  4599.6    62.5  4619.6    61.7  4649.6    61.6  4689.6      61
  4719.6    61.7  4739.6    61.8  4769.6    62.7  4809.6      62  4839.6    62.5
  4953.4    63.2  4976.8   61.24  4987.9   59.08  4989.8   56.39  4994.2   54.44
  5000.3   54.85  5008.8   54.86  5010.1   56.41  5014.9    58.3  5032.8    61.3
  5043.4    61.8  5053.4    63.2  5073.4    63.2  5093.4    62.5  5542.1    64.2
#Mann= 5 , 1 , 0
  4180.2      .2       0  4529.7      .1       0  4976.8     .04       0
  5032.8      .1       0  5542.1      .2       0
#XS Ineff= 2 , 0
       0  4752.9    62.2               0
Permanent Ineff=
       F       F
Bank Sta=4976.8,5032.8
XS Rating Curve= 0
Exp/Cntr=.3,.1

Type RM Length L Ch R = 1 ,21739.1 ,148.1,165.3,155.8
BEGIN DESCRIPTION:
Cross Section 21739.1-Interpolated
END DESCRIPTION:
XS GIS Cut Line= 5
      3142919.37     13886842.96      3142869.26     13886399.45
      3142883.91     13886106.48      3142869.26     13885886.76
       3142712.6     13885041.02
#Sta/Elev= 30
  4204.3    62.8  4720.6    62.5  4790.6    61.7  4830.6    59.6  4880.6      62
    4964    62.5  4976.8   60.21  4982.9   57.84  4987.9   58.05  4989.8   55.36
  4994.2   53.41  5008.8   53.83  5010.1   55.38  5013.7   55.97  5014.9   57.27
  5032.8   60.27    5034    62.6    5134    61.4  5194.2    59.1  5234.2    61.2
  5414.2    61.2  5474.2    59.1  5494.2      61  5644.2    61.7  5764.2    60.2
  5774.2    61.1  5974.2    61.1  5994.2    59.6  6015.6    60.9  6024.3    62.5
#Mann= 4 , 1 , 0
  4204.3      .1       0  4976.8     .04       0  5032.8      .1       0
  6015.6      .2       0
#XS Ineff= 2 , 0
       0  4877.1    61.8  5067.3       0    62.2
Permanent Ineff=
       F       F
Bank Sta=4976.8,5032.8
XS Rating Curve= 0
Exp/Cntr=.5,.3

Type RM Length L Ch R = 1 ,21573.8 ,55,55,55
BEGIN DESCRIPTION:
Upstream Section of Bridge/Culvert/Weir
END DESCRIPTION:
XS GIS Cut Line= 5
      3143016.65      13886861.6      3143022.18     13886676.63
      3143042.34      13886100.7      3143061.88      13885690.4
      3143111.08     13885073.66
#Sta/Elev= 30
    4194   62.61  4711.6   61.81  4811.4   58.26  4838.4   58.25  4843.7   59.95
  4976.8   60.01  4982.9   57.64  4987.9   57.85  4989.8   55.16  4994.2   53.21
  5008.8   53.63  5010.1   55.18  5013.7   55.77  5014.9   57.07  5032.8   60.07
  5147.6   60.47  5163.9   57.73  5191.3   57.91  5201.5   59.84  5279.7   62.01
  5409.7   61.31  5444.3   58.51  5484.3   61.01  5664.3   61.71  5704.3   60.01
  5954.3   61.11  5964.3   59.61  5974.3   59.61  5983.3   60.71  5984.8   62.21
#Mann= 3 , 1 , 0
    4194      .1       0  4976.8     .04       0  5032.8      .1       0
#XS Ineff= 2 , 0
       0    4970   58.79  5279.7       0      62
Permanent Ineff=
       F       F
Bank Sta=4976.8,5032.8
XS Rating Curve= 0
Exp/Cntr=.5,.3

Type RM Length L Ch R = 3 ,21546.3 ,,,
BEGIN DESCRIPTION:
CHEEVES DRIVE
Structure ID:
END DESCRIPTION:
Bridge Culvert--1,0,-1,-1, 0
Deck Dist Width WeirC Skew NumUp NumDn MinLoCord MaxHiCord MaxSubmerge Is_Ogee
10,35,2.6,0, 49, 49, , , .95, 0, 1,1,,
    4194    4284    4324    4424    4554  4711.6    4773  4810.5  4811.4  4838.4
  4839.3  4843.7  4894.3  4954.2  4976.8  4981.8  4981.9  5006.3 5029.49  5029.6
  5032.8  5052.4  5086.9  5147.6  5162.9  5163.6  5163.9    5171  5191.3  5192.1
  5192.7  5201.5  5232.6  5279.7  5409.7  5424.3  5444.3  5454.3  5484.3  5664.3
  5684.3  5704.3  5724.3  5764.3  5954.3  5964.3  5974.3  5983.3  5984.8
    62.6    62.2   62.61   62.01   62.41   61.81   60.08   58.89   58.89   58.93
   58.93   59.95   60.46   60.13   60.46   60.55   60.55   60.67    60.9    60.9
   60.88   60.79   60.86   60.47   58.63   58.62   58.62   58.56   58.61   58.61
   58.76   59.84    60.3   62.01   61.31   60.61   59.19   59.21   61.01   61.71
   61.21      60    60.2      61    61.1    59.6    59.6    60.7    62.2
    62.6    62.2    62.6      62    62.4    61.8   60.07   58.76   58.25   58.24
    58.7   59.94   60.45   60.12      60   58.06    59.6   59.72   59.95   59.54
   60.06   60.35   60.85   60.46   58.58   58.39   57.72   57.77    57.9   58.43
   58.75   59.83   60.29      62    61.3    60.6    58.5    58.6      61    61.7
    61.2      60    60.2      61    61.1    59.6    59.6    60.7    62.2
    4194    4284    4324    4424    4554  4711.6    4773  4810.5  4811.4  4838.4
  4839.3  4843.7  4894.3  4954.2  4976.8  4981.8  4981.9  5006.3 5029.49  5029.6
  5032.8  5052.4  5086.9  5147.6  5162.9  5163.6  5163.9    5171  5191.3  5192.1
  5192.7  5201.5  5232.6  5279.7  5409.7  5424.3  5444.3  5454.3  5484.3  5664.3
  5684.3  5704.3  5724.3  5764.3  5954.3  5964.3  5974.3  5983.3  5984.8
    62.6    62.2   62.61   62.01   62.41   61.81   60.08   58.89   58.89   58.93
   58.93   59.95   60.46   60.13   60.46   60.55   60.55   60.67    60.9    60.9
   60.88   60.79   60.86   60.47   58.63   58.62   58.62   58.56   58.61   58.61
   58.76   59.84    60.3   62.01   61.31   60.61   59.19   59.21   61.01   61.71
   61.21      60    60.2      61    61.1    59.6    59.6    60.7    62.2
    62.5    62.1    62.5    61.9    62.3    61.7   59.97   58.66   58.15   58.14
    58.6   59.84   60.35   60.02    59.9   57.96    59.5   59.62   59.85   59.44
   59.96   60.25   60.75   60.36   58.48   58.29   57.62   57.67    57.8   58.33
   58.65   59.73   60.19    61.9    61.2    60.5    58.4    58.5    60.9    61.6
    61.1    59.9    60.1    60.9      61    59.5    59.5    60.6    62.1
Pier Skew, UpSta & Num, DnSta & Num=  ,4997.9, 2 ,4997.9, 2 , 0 , 0 , 0 ,,
       1       1
   52.34   60.68
       1       1
   52.24   60.58
Pier Skew, UpSta & Num, DnSta & Num=  ,5013.7, 2 ,5013.7, 2 , 0 , 0 , 0 ,,
       1       1
   54.68    60.8
       1       1
   54.58    60.7
Abutment Skew #Up #Dn= , 2 , 2
  4981.7  4982.9
    59.6   57.63
  4981.7  4982.9
    59.5   57.53
Abutment Skew #Up #Dn= , 2 , 2
  5017.5 5029.69
   57.58   59.95
  5017.5 5029.69
   57.48   59.85
BR Coef= 1 , 1 , 0 ,1.25, 0 ,,,.8,0,2,0,
WSPro=,,,, 1 ,,,, 0 ,,,, 0 ,,,,-1 ,-1 ,-1 , 0 , 0 , 0 , 0 , 0
BR U #Sta/Elev= 81
    4194    62.6    4284    62.2  4302.3   62.38    4324    62.6    4424      62
    4554    62.4  4711.6    61.8  4772.8   60.07  4772.9   60.07    4773   60.07
  4810.5   58.76  4811.4   58.25  4836.2   58.24  4838.4   58.24  4839.3    58.7
  4843.7   59.94  4893.1   60.44  4894.3   60.45  4954.2   60.12  4976.8      60
  4981.5   58.17 4981.61   58.13 4981.69    58.1  4981.8   58.06  4981.9   58.02
 4982.01   57.98  4982.8   57.67  4982.9   57.63  4987.9   57.84  4989.8   55.15
  4994.2    53.2  4997.8   53.36  5000.2   53.61  5006.3   53.62  5008.8   53.62
  5010.1   55.17  5013.7   55.76  5014.9   57.06  5017.4   57.56  5017.5   57.58
 5029.09   59.46  5029.2   59.48 5029.31   59.49 5029.49   59.52  5029.6   59.54
  5029.7   59.56  5032.8   60.06  5052.4   60.35  5086.9   60.85  5112.5   60.69
  5147.6   60.46  5162.9   58.58  5163.6   58.39  5163.9   57.72    5171   57.77
  5191.3    57.9  5192.1   58.43  5192.7   58.75  5201.5   59.83  5232.6   60.29
  5233.8   60.33  5279.7      62  5409.7    61.3  5424.3    60.6  5444.3    58.5
  5454.3    58.6  5484.3      61  5580.3   61.37  5610.3   61.49  5640.3   61.61
  5664.3    61.7  5684.3    61.2  5685.3   61.14  5704.3      60  5724.3    60.2
  5764.3      61  5954.3    61.1  5964.3    59.6  5974.3    59.6  5983.3    60.7
  5984.8    62.2
BR U #Mann= 3
    4194      .1  4976.8     .04  5032.8      .1
BR U Banks=4976.8,5032.8
BR D #Sta/Elev= 81
    4194    62.5    4284    62.1  4302.3   62.28    4324    62.5    4424    61.9
    4554    62.3  4711.6    61.7  4772.8   59.97  4772.9   59.97    4773   59.97
  4810.5   58.66  4811.4   58.15  4836.2   58.14  4838.4   58.14  4839.3    58.6
  4843.7   59.84  4893.1   60.34  4894.3   60.35  4954.2   60.02  4976.8    59.9
  4981.5   58.07 4981.61   58.03 4981.69      58  4981.8   57.96  4981.9   57.92
 4982.01   57.88  4982.8   57.57  4982.9   57.53  4987.9   57.74  4989.8   55.05
  4994.2    53.1  4997.8   53.26  5000.2   53.51  5006.3   53.52  5008.8   53.52
  5010.1   55.07  5013.7   55.66  5014.9   56.96  5017.4   57.46  5017.5   57.48
 5029.09   59.36  5029.2   59.38 5029.31   59.39 5029.49   59.42  5029.6   59.44
  5029.7   59.46  5032.8   59.96  5052.4   60.25  5086.9   60.75  5112.5   60.59
  5147.6   60.36  5162.9   58.48  5163.6   58.29  5163.9   57.62    5171   57.67
  5191.3    57.8  5192.1   58.33  5192.7   58.65  5201.5   59.73  5232.6   60.19
  5233.8   60.23  5279.7    61.9  5409.7    61.2  5424.3    60.5  5444.3    58.4
  5454.3    58.5  5484.3    60.9  5580.3   61.27  5610.3   61.39  5640.3   61.51
  5664.3    61.6  5684.3    61.1  5685.3   61.04  5704.3    59.9  5724.3    60.1
  5764.3    60.9  5954.3      61  5964.3    59.5  5974.3    59.5  5983.3    60.6
  5984.8    62.1
BR D #Mann= 3
    4194      .1  4976.8     .04  5032.8      .1
BR D Banks=4976.8,5032.8
BC Design=,, 0 ,, 0 ,,,,,,

Type RM Length L Ch R = 1 ,21518.8 ,549,549,549
BEGIN DESCRIPTION:
Downstream Section of Bridge/Culvert/Weir
END DESCRIPTION:
XS GIS Cut Line= 5
      3143071.62     13886863.44      3143077.14     13886678.47
       3143097.3     13886102.54      3143116.84     13885692.24
      3143166.05      13885075.5
#Sta/Elev= 30
    4194   62.49  4711.6   61.69  4811.4   58.14  4838.4   58.13  4843.7   59.83
  4976.8   59.89  4982.9   57.52  4987.9   57.73  4989.8   55.04  4994.2   53.09
  5008.8   53.51  5010.1   55.06  5013.7   55.65  5014.9   56.95  5032.8   59.95
  5147.6   60.35  5163.9   57.61  5191.3   57.79  5201.5   59.72  5279.7   61.89
  5409.7   61.19  5444.3   58.39  5484.3   60.89  5664.3   61.59  5704.3   59.89
  5954.3   60.99  5964.3   59.49  5974.3   59.49  5983.3   60.59  5984.8   62.09
#Mann= 3 , 1 , 0
    4194      .1       0  4976.8     .04       0  5032.8      .1       0
#XS Ineff= 2 , 0
       0    4970   58.79  5279.7       0    61.9
Permanent Ineff=
       F       F
Bank Sta=4976.8,5032.8
XS Rating Curve= 0
Exp/Cntr=.5,.3

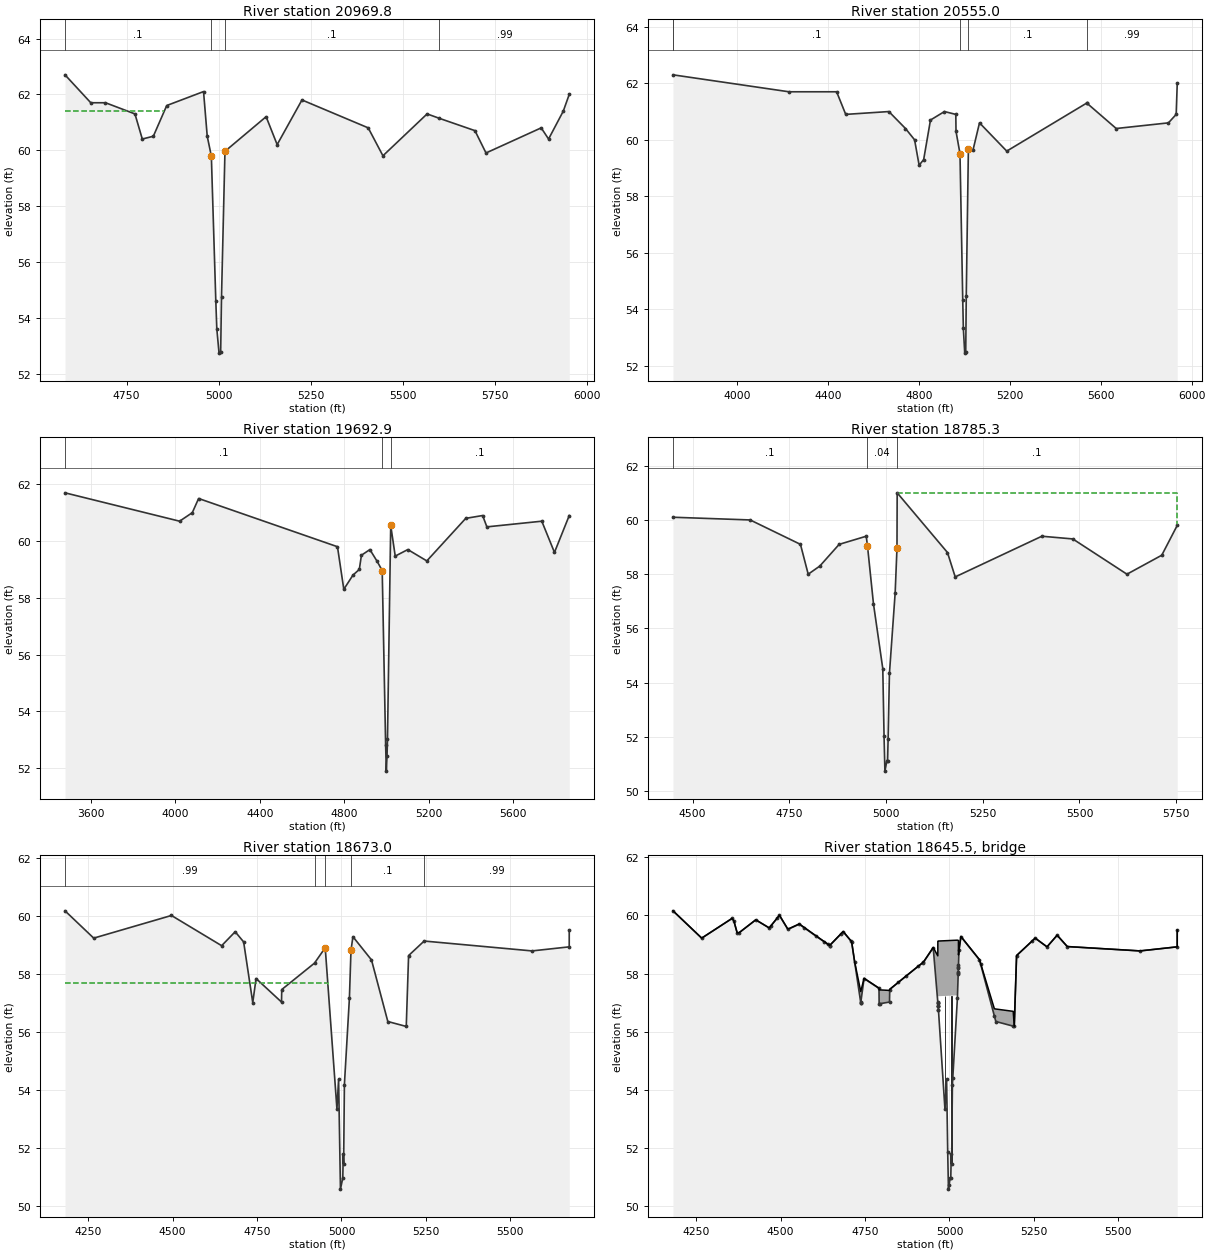
Type RM Length L Ch R = 1 ,20969.8 ,438.3,414.8,381.1
BEGIN DESCRIPTION:
Cross Section 20969.8-Interpolated
END DESCRIPTION:
XS GIS Cut Line= 4
      3143676.98     13886484.97      3143660.27     13886209.02
      3143630.98     13885842.82      3143403.78      13885153.1
#Sta/Elev= 29
  4582.6    62.7  4652.6    61.7  4692.6    61.7  4772.6    61.3  4792.6    60.4
  4822.6    60.5    4859    61.6    4959    62.1    4969    60.5  4980.2   59.79
  4992.3   54.61    4995   53.61  5001.1   52.73  5005.5   52.76  5007.8   54.74
  5017.2   59.96    5129    61.2    5159    60.2  5226.4    61.8  5406.4    60.8
  5446.4    59.8  5566.4    61.3    5600   61.14  5696.4    60.7  5726.4    59.9
  5876.4    60.8  5896.4    60.4  5936.4    61.4  5952.6      62
#Mann= 4 , 1 , 0
  4582.6      .1       0  4980.2     .04       0  5017.2      .1       0
    5600     .99       0
#XS Ineff= 2 , 0
       0 4852.38    61.4  5298.4       0    61.4
Permanent Ineff=
       F       F
Bank Sta=4980.2,5017.2
XS Rating Curve= 0
Exp/Cntr=.3,.1

Type RM Length L Ch R = 1 ,20555.0 ,870.1,862.1,861
BEGIN DESCRIPTION:
Cross Section 20555.0
END DESCRIPTION:
XS GIS Cut Line= 6
      3144102.92       13887201.      3144138.38     13886691.87
      3144107.46     13886179.57      3144072.13     13886011.74
      3143768.55     13885465.05      3143628.15     13885091.92
#Sta/Elev= 29
  3716.7    62.3  4227.1    61.7  4437.1    61.7  4477.1    60.9  4667.1      61
  4740.3    60.4  4780.3      60  4800.3    59.1  4820.3    59.3  4850.3    60.7
  4911.8      61  4961.8    60.9  4962.7    60.3  4980.2   59.51  4992.3   54.33
    4995   53.33  5001.1   52.45  5005.5   52.48  5007.8   54.46  5017.2   59.68
  5037.6   59.64  5066.1    60.6  5186.1    59.6    5538    61.3    5540   61.29
    5668    60.4    5898    60.6    5932    60.9  5936.7      62
#Mann= 5 , 1 , 0
  3716.7      .2       0  3716.7      .1       0  4980.2     .04       0
  5017.2      .1       0    5540     .99       0
#XS Ineff= 2 , 0
       0  4911.8      61    5538       0    61.3
Permanent Ineff=
       F       F
Bank Sta=4980.2,5017.2
XS Rating Curve= 0
Exp/Cntr=.3,.1

Type RM Length L Ch R = 1 ,19692.9 ,904.7,907.6,921.4
BEGIN DESCRIPTION:
Cross Section 19692.9
END DESCRIPTION:
XS GIS Cut Line= 6
      3144759.46     13887075.23      3144768.07     13886532.81
      3144866.64     13885718.04       3144830.4     13885588.59
      3144637.43     13885238.87      3144446.85     13884787.54
#Sta/Elev= 26
  3478.3    61.7  4020.8    60.7  4080.8      61  4110.8    61.5  4768.1    59.8
  4798.1    58.3  4841.5    58.8  4871.5      59  4881.5    59.5  4921.5    59.7
 4956.25   59.28 4979.85   58.96 4996.15    52.8 4999.35   51.89 5002.75   52.44
 5004.85   53.02 5020.15   60.55 5041.55   59.47  5101.1    59.7  5191.1    59.3
  5375.3    60.8  5455.3    60.9  5475.3    60.5  5735.3    60.7  5795.3    59.6
  5865.3    60.9
#Mann= 3 , 1 , 0
  3478.3      .1       0 4979.85     .04       0 5020.15      .1       0
#XS Ineff= 2 , 0
       0  4921.5    59.7  5735.3       0    60.7
Permanent Ineff=
       F       F
Bank Sta=4979.85,5020.15
XS Rating Curve= 0
Exp/Cntr=.3,.1

Type RM Length L Ch R = 1 ,18785.3 ,112.1,112.3,164
BEGIN DESCRIPTION:
Cross Section 18785.3-Interpolated
END DESCRIPTION:
XS GIS Cut Line= 5
      3145840.32     13885697.36      3145840.33     13885697.33
      3145784.28      13885505.9      3145476.66     13884817.43
      3145342.67     13884494.17
#Sta/Elev= 26
  4449.2    60.1  4648.7      60  4778.7    59.1  4798.7      58  4828.7    58.3
  4878.7    59.1  4948.7    59.4  4951.9   59.05  4967.4   56.91  4991.5   54.52
  4994.8   52.03    4997   50.74  5002.2   51.13  5003.9   51.12  5005.3   51.94
  5008.7   54.34  5023.5   57.31  5028.2   58.96  5028.7      61  5158.7    58.8
  5178.7    57.9  5402.7    59.4  5482.7    59.3  5622.7      58  5712.7    58.7
  5752.7    59.8
#Mann= 3 , 1 , 0
  4449.2      .1       0  4951.9     .04       0  5028.2      .1       0
#XS Ineff= 2 , 0
       0  4948.7    59.4  5028.7       0      61
Permanent Ineff=
       F       F
Bank Sta=4951.9,5028.2
XS Rating Curve= 0
Exp/Cntr=.5,.3

Type RM Length L Ch R = 1 ,18673.0 ,55,55,55
BEGIN DESCRIPTION:
Upstream Section of Bridge/Culvert/Weir
END DESCRIPTION:
XS GIS Cut Line= 6
      3145866.74     13885914.48      3145920.86     13885691.35
      3145925.64     13885612.37      3145918.86     13885533.22
      3145701.78     13885035.76      3145702.95     13884474.41
#Sta/Elev= 30
  4181.6   60.17  4266.6   59.23  4496.7   60.01  4645.3   58.97  4685.4   59.45
  4710.4    59.1  4737.4   57.01  4747.2   57.84  4822.5   57.03  4823.2   57.46
  4920.2   58.37  4951.9    58.9  4986.6   53.35  4991.5   54.37    4997   50.59
  5003.9   50.97  5005.3   51.79  5006.4   51.47  5008.7   54.19  5023.5   57.16
  5028.2   58.81  5033.9   59.28  5088.9   58.48  5137.2   56.36  5191.8   56.19
  5198.7   58.63  5244.8   59.13  5564.2   58.79  5674.2   58.93  5674.3   59.51
#Mann= 5 , 1 , 0
  4181.6     .99       0  4920.2      .1       0  4951.9     .04       0
  5028.2      .1       0  5244.8     .99       0
#XS Ineff= 2 , 0
       0 4960.46    57.7  5024.7       0    57.5
Permanent Ineff=
       F       F
Bank Sta=4951.9,5028.2
XS Rating Curve= 0
Exp/Cntr=.5,.3

Type RM Length L Ch R = 3 ,18645.5 ,,,
BEGIN DESCRIPTION:
BURNINGBUSH LANE
Structure ID: P25-8,,,,
END DESCRIPTION:
Bridge Culvert--1,0,-1,-1, 0
Deck Dist Width WeirC Skew NumUp NumDn MinLoCord MaxHiCord MaxSubmerge Is_Ogee
10,35,2.6,0, 45, 45, , , .95, 0, 1,1,,
  4181.6  4266.6  4356.6  4361.6  4371.6  4376.6  4426.6  4466.6  4496.7  4521.7
  4555.3  4645.3  4685.4  4710.4  4719.3  4737.4  4747.2  4791.4  4791.8  4822.5
  4823.2  4923.1  4951.9 4965.49  4965.6 4966.41  4966.5  5023.5  5026.6 5026.71
  5028.2  5033.9  5088.9  5132.9  5137.2  5188.7  5191.8  5198.7  5253.8  5288.8
  5318.8  5348.8  5564.2  5674.2  5674.3
   60.16   59.22    59.9   59.82    59.4    59.4   59.85   59.57   60.01   59.53
   59.71   58.97   59.45    59.1   58.41   57.38   57.84    57.5   57.44   57.42
   57.46    58.4    58.9   58.61   59.11   59.12   59.12   59.15   59.14   58.64
   58.81   59.28   58.48   56.79   56.78    56.7   56.18   58.62   59.22   58.92
   59.32   58.93   58.78   58.92    59.5
   60.16   59.22    59.9   59.82    59.4    59.4   59.85   59.57      60   59.52
    59.7   58.96   59.44   59.09    58.4      57   57.83   57.49   56.96   57.02
   57.45   58.39   58.89   57.01      57   56.89   57.22   57.25   58.24   58.28
    58.8   59.27   58.47   56.54   56.35   56.19   56.18   58.62   59.22   58.92
   59.32   58.93   58.78   58.92    59.5
  4181.6  4266.6  4356.6  4361.6  4371.6  4376.6  4426.6  4466.6  4496.7  4521.7
  4555.3  4645.3  4685.4  4710.4  4719.3  4737.4  4747.2  4791.4  4791.8  4822.5
  4823.2  4923.1  4951.9 4965.49  4965.6 4966.41  4966.5  5023.5  5026.6 5026.71
  5028.2  5033.9  5088.9  5132.9  5137.2  5188.7  5191.8  5198.7  5253.8  5288.8
  5318.8  5348.8  5564.2  5674.2  5674.3
   60.16   59.22    59.9   59.82    59.4    59.4   59.85   59.57   60.01   59.53
   59.71   58.97   59.45    59.1   58.41   57.38   57.84    57.5   57.44   57.42
   57.46    58.4    58.9   58.61   59.11   59.12   59.12   59.15   59.14   58.64
   58.81   59.28   58.48   56.79   56.78    56.7   56.18   58.62   59.22   58.92
   59.32   58.93   58.78   58.92    59.5
   60.06   59.12    59.8   59.72    59.3    59.3   59.75   59.47    59.9   59.42
    59.6   58.86   59.34   58.99    58.3    56.9   57.73   57.39   56.86   56.92
   57.35   58.29   58.79   56.91    56.9   56.79   57.12   57.15   58.14   58.18
    58.7   59.17   58.37   56.44   56.25   56.09   56.08   58.52   59.12   58.82
   59.22   58.83   58.68   58.82    59.4
Pier Skew, UpSta & Num, DnSta & Num=  ,4986.6, 2 ,4986.6, 2 , 0 , 0 , 0 ,,
     1.2     1.2
   52.45   58.23
     1.2     1.2
   52.35   58.13
Pier Skew, UpSta & Num, DnSta & Num=  ,5006.4, 2 ,5006.4, 2 , 0 , 0 , 0 ,,
     1.2     1.2
   50.63   58.24
     1.2     1.2
   50.53   58.14
Abutment Skew #Up #Dn= , 2 , 2
  4966.3  4967.4
   57.22   56.75
  4966.3  4967.4
   57.12   56.65
Abutment Skew #Up #Dn= , 2 , 2
  5009.8 5026.09
    54.4   57.99
  5009.8 5026.09
    54.3   57.89
BR Coef= 1 , 1 , 0 ,1.25, 0 ,,,.8,0,2,0,
WSPro=,,,, 1 ,,,, 0 ,,,, 0 ,,,,-1 ,-1 ,-1 , 0 , 0 , 0 , 0 , 0
BR U #Sta/Elev= 82
  4181.6   60.16  4266.6   59.22  4356.6    59.9  4361.6   59.82  4371.6    59.4
  4376.6    59.4  4426.6   59.85  4466.6   59.57  4471.7   59.65  4490.3   59.91
  4496.7      60  4521.7   59.52  4555.3    59.7  4569.7   59.58  4604.7   59.29
  4629.7   59.09  4639.7   59.01  4645.3   58.96  4645.4   58.96  4679.3   59.37
  4685.4   59.44  4709.3   59.11  4710.4   59.09  4719.3    58.4  4737.4      57
  4737.5      57  4737.8   57.03  4747.2   57.83  4791.4   57.49  4791.8   56.96
  4793.1   56.96  4822.5   57.02  4823.2   57.45  4849.1    57.7  4872.2   57.92
  4907.4   58.25  4920.2   58.36  4923.1   58.39  4951.9   58.89 4965.49   57.01
  4965.6      57 4965.71   56.98  4966.3    56.9 4966.41   56.89  4966.5   56.87
  4967.3   56.76  4967.4   56.75  4986.6   53.34  4991.5   54.36  4994.8   51.87
    4997   50.58  4998.7   50.71  5002.2   50.97  5003.9   50.96  5005.3   51.78
  5006.4   51.46  5008.7   54.18  5009.8    54.4  5023.5   57.15 5025.89   57.99
    5026   58.03  5026.1   58.06 5026.49    58.2  5026.6   58.24 5026.71   58.28
  5028.2    58.8  5033.9   59.27  5088.9   58.47  5091.9   58.34  5132.9   56.54
  5137.2   56.35  5188.7   56.19  5191.8   56.18  5198.7   58.62  5244.8   59.12
  5253.8   59.22  5288.8   58.92  5318.8   59.32  5348.8   58.93  5564.2   58.78
  5674.2   58.92  5674.3    59.5
BR U #Mann= 5
  4181.6     .99  4920.2      .1  4951.9     .04  5028.2      .1  5244.8     .99
BR U Banks=4951.9,5028.2
BR D #Sta/Elev= 82
  4181.6   60.06  4266.6   59.12  4356.6    59.8  4361.6   59.72  4371.6    59.3
  4376.6    59.3  4426.6   59.75  4466.6   59.47  4471.7   59.55  4490.3   59.81
  4496.7    59.9  4521.7   59.42  4555.3    59.6  4569.7   59.48  4604.7   59.19
  4629.7   58.99  4639.7   58.91  4645.3   58.86  4645.4   58.86  4679.3   59.27
  4685.4   59.34  4709.3   59.01  4710.4   58.99  4719.3    58.3  4737.4    56.9
  4737.5    56.9  4737.8   56.93  4747.2   57.73  4791.4   57.39  4791.8   56.86
  4793.1   56.86  4822.5   56.92  4823.2   57.35  4849.1    57.6  4872.2   57.82
  4907.4   58.15  4920.2   58.26  4923.1   58.29  4951.9   58.79 4965.49   56.91
  4965.6    56.9 4965.71   56.88  4966.3    56.8 4966.41   56.79  4966.5   56.77
  4967.3   56.66  4967.4   56.65  4986.6   53.24  4991.5   54.26  4994.8   51.77
    4997   50.48  4998.7   50.61  5002.2   50.87  5003.9   50.86  5005.3   51.68
  5006.4   51.36  5008.7   54.08  5009.8    54.3  5023.5   57.05 5025.89   57.89
    5026   57.93  5026.1   57.96 5026.49    58.1  5026.6   58.14 5026.71   58.18
  5028.2    58.7  5033.9   59.17  5088.9   58.37  5091.9   58.24  5132.9   56.44
  5137.2   56.25  5188.7   56.09  5191.8   56.08  5198.7   58.52  5244.8   59.02
  5253.8   59.12  5288.8   58.82  5318.8   59.22  5348.8   58.83  5564.2   58.68
  5674.2   58.82  5674.3    59.4
BR D #Mann= 5
  4181.6     .99  4920.2      .1  4951.9     .04  5028.2      .1  5244.8     .99
BR D Banks=4951.9,5028.2
BC Design=,, 0 ,, 0 ,,,,,,