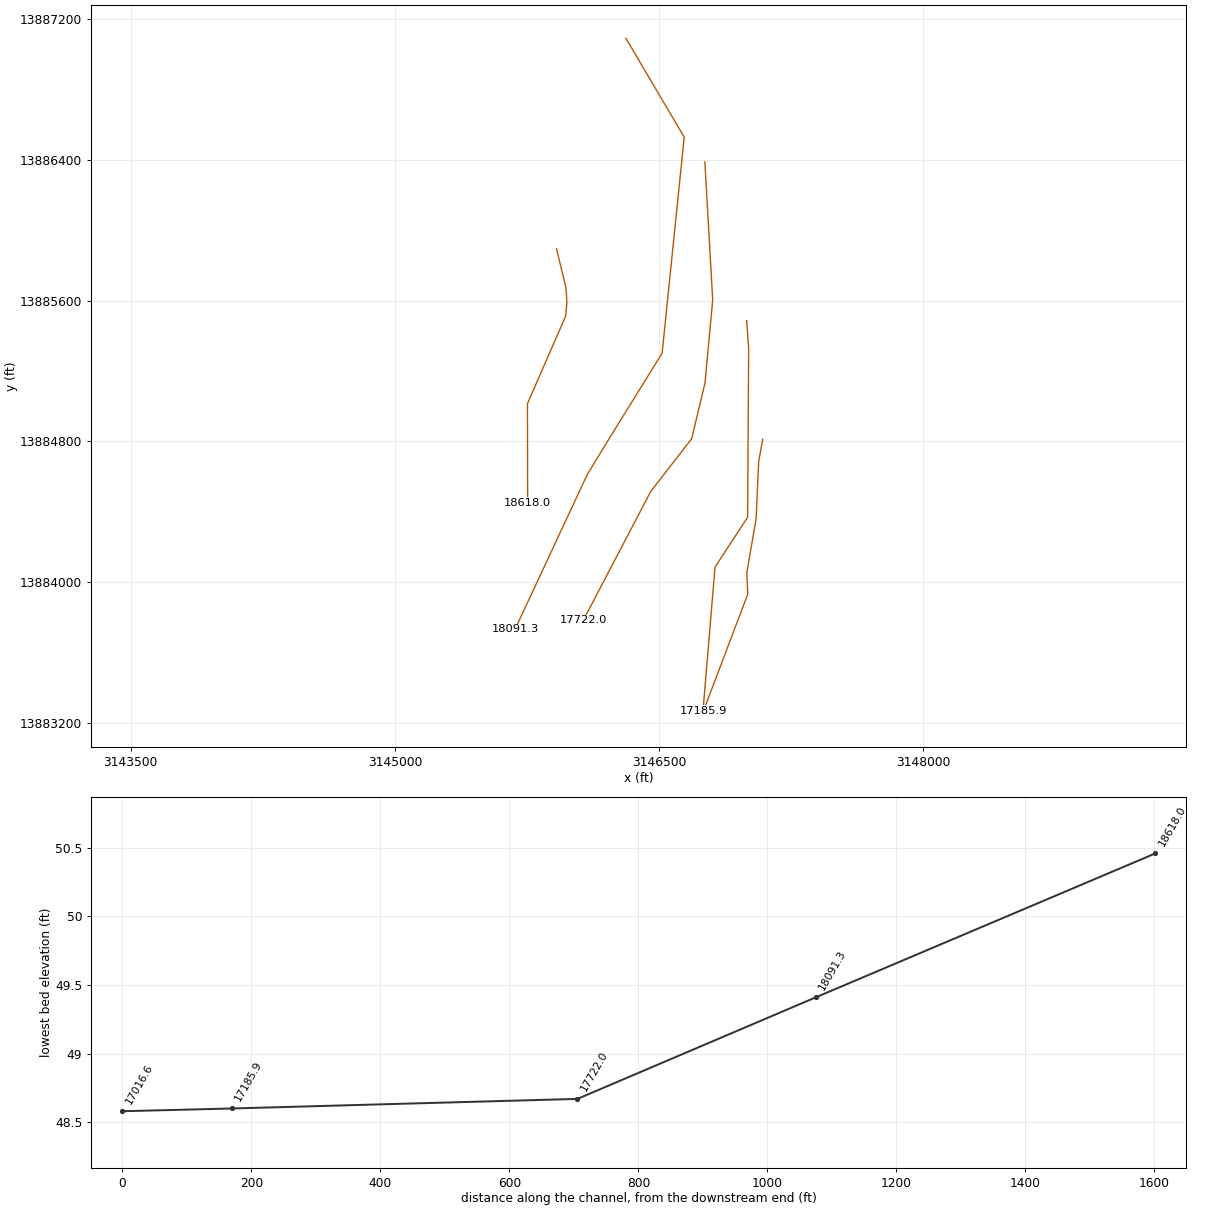
HEC-RAS study P125-00-00.PRJ: P125-00-00

--- P125-00-00.g01 (geometry) --- (continued)

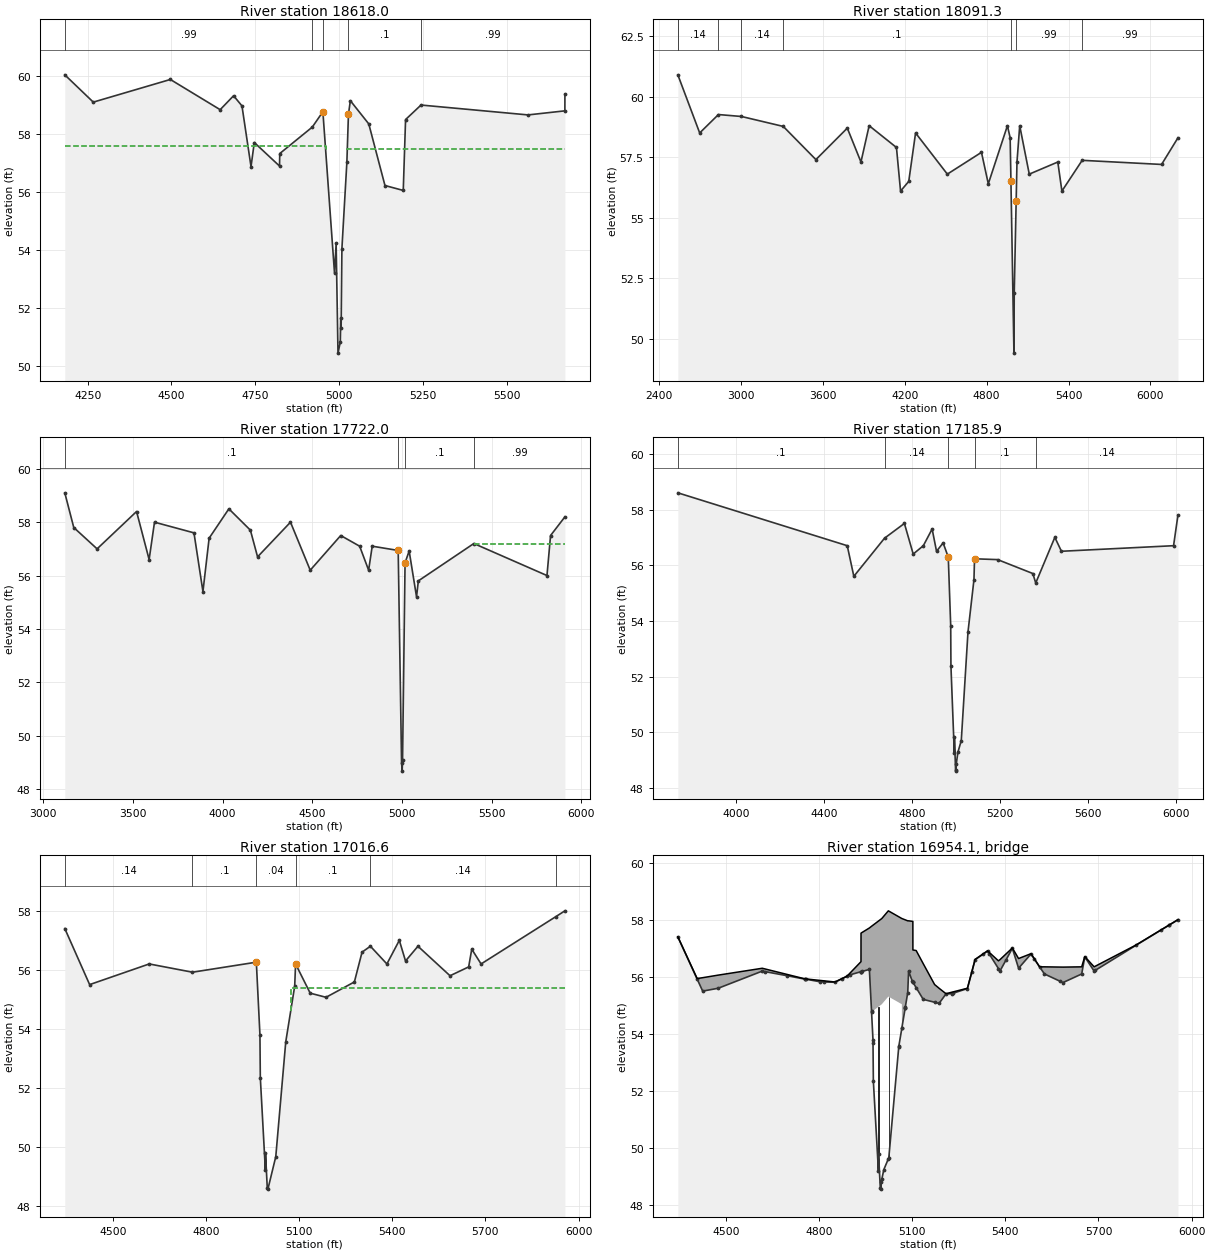
Type RM Length L Ch R = 1 ,18618.0 ,526.7,526.7,526.7
BEGIN DESCRIPTION:
Downstream Section of Bridge/Culvert/Weir
END DESCRIPTION:
XS GIS Cut Line= 6
      3145917.42     13885893.12      3145971.54     13885669.99
      3145976.32     13885591.01      3145969.54     13885511.86
      3145752.46      13885014.4      3145753.63     13884453.05
#Sta/Elev= 30
  4181.6   60.04  4266.6    59.1  4496.7   59.88  4645.3   58.84  4685.4   59.32
  4710.4   58.97  4737.4   56.88  4747.2   57.71  4822.5    56.9  4823.2   57.33
  4920.2   58.24  4951.9   58.77  4986.6   53.22  4991.5   54.24    4997   50.46
  5003.9   50.84  5005.3   51.66  5006.4   51.34  5008.7   54.06  5023.5   57.03
  5028.2   58.68  5033.9   59.15  5088.9   58.35  5137.2   56.23  5191.8   56.06
  5198.7    58.5  5244.8      59  5564.2   58.66  5674.2    58.8  5674.3   59.38
#Mann= 5 , 1 , 0
  4181.6     .99       0  4920.2      .1       0  4951.9     .04       0
  5028.2      .1       0  5244.8     .99       0
#XS Ineff= 2 , 0
       0 4960.46    57.6  5024.7       0   57.47
Permanent Ineff=
       F       F
Bank Sta=4951.9,5028.2
XS Rating Curve= 0
Exp/Cntr=.5,.3

Type RM Length L Ch R = 1 ,18091.3 ,386.8,369.3,362
BEGIN DESCRIPTION:
Cross Section 18091.3-Interpolated
END DESCRIPTION:
XS GIS Cut Line= 6
      3146311.28     13887087.76      3146642.07      13886527.1
      3146516.69     13885300.83      3146253.02     13884876.03
      3146091.89     13884612.36      3145681.74     13883733.46
#Sta/Elev= 30
    2539    60.9    2699    58.5  2836.3   59.26  3005.1   59.18    3311   58.77
    3550    57.4    3780    58.7    3880    57.3    3940    58.8    4140    57.9
    4170    56.1    4230    56.5    4280    58.5  4512.6    56.8  4762.6    57.7
  4812.6    56.4  4952.6    58.8  4972.6    58.3  4978.3   56.53  5000.4   49.41
  5002.6    51.9  5016.6   55.68  5022.6    57.3  5042.6    58.8  5112.6    56.8
  5321.6    57.3  5351.6    56.1    5500   57.37  6081.6    57.2  6201.5    58.3
#Mann= 8 , 1 , 0
    2539      .2       0    2539     .14       0  2836.3      .1       0
  3005.1     .14       0    3311      .1       0  4978.3     .04       0
  5016.6     .99       0    5500     .99       0
#XS Ineff= 2 , 0
       0    4280    58.5               0
Permanent Ineff=
       F       F
Bank Sta=4978.3,5016.6
XS Rating Curve= 0
Exp/Cntr=.3,.1

Type RM Length L Ch R = 1 ,17722.0 ,516.8,536.1,627.4
BEGIN DESCRIPTION:
Cross Section 17722.0
END DESCRIPTION:
XS GIS Cut Line= 6
       3146759.3     13886386.78      3146803.77     13885603.47
      3146759.99       13885132.      3146684.39     13884815.43
      3146452.87     13884517.76       3146069.6     13883785.42
#Sta/Elev= 30
    3120    59.1    3170    57.8    3300      57    3520    58.4    3590    56.6
    3620      58    3840    57.6    3890    55.4  3924.5    57.4  4034.5    58.5
  4154.5    57.7  4194.5    56.7    4378      58    4488    56.2    4658    57.5
  4763.5    57.1  4813.5    56.2  4833.5    57.1  4978.3   56.94  4997.1   48.99
  5000.4   48.67  5002.6   49.08  5016.6   56.48  5039.5   56.92  5080.6    55.2
  5090.6    55.8    5400    57.2  5807.6      56  5827.6    57.5  5907.6    58.2
#Mann= 4 , 1 , 0
    3120      .1       0  4978.3     .04       0  5016.6      .1       0
    5400     .99       0
#XS Ineff= 2 , 0
       0    4658    57.5  5400.6       0    57.2
Permanent Ineff=
       F       F
Bank Sta=4978.3,5016.6
XS Rating Curve= 0
Exp/Cntr=.3,.1

Type RM Length L Ch R = 1 ,17185.9 ,66.7,169.3,162.8
BEGIN DESCRIPTION:
Cross Section 17185.9-Interpolated
END DESCRIPTION:
XS GIS Cut Line= 5
      3146996.57     13885486.36      3147007.76      13885326.3
      3147002.03     13884370.19        3146817.     13884087.19
      3146748.61     13883270.05
#Sta/Elev= 30
  3734.3    58.6  4504.8    56.7  4534.8    55.6  4674.4   56.97  4764.8    57.5
  4804.8    56.4  4850.9    56.7  4890.9    57.3  4910.9    56.5  4940.9    56.8
 4964.29   56.29 4975.35   53.83 4976.41   52.38 4991.81   49.24 4992.14   49.84
 4997.62   48.63 4999.51    48.6 5000.74   48.86 5008.19   49.28 5023.51    49.7
 5053.97    53.6 5081.16   55.48 5083.78   56.23    5189    56.2    5349    55.7
  5362.1   55.36    5449      57    5479    56.5    5989    56.7    6009    57.8
#Mann= 5 , 1 , 0
  3734.3      .1       0  4674.4     .14       0 4964.29     .04       0
 5083.78      .1       0  5362.1     .14       0
#XS Ineff= 2 , 0
       0  4764.8    57.5    5449       0      57
Permanent Ineff=
       F       F
Bank Sta=4964.29,5083.78
XS Rating Curve= 0
Exp/Cntr=.5,.3

Type RM Length L Ch R = 1 ,17016.6 ,125,125,125
BEGIN DESCRIPTION:
Upstream Section of Bridge/Culvert/Weir
END DESCRIPTION:
XS GIS Cut Line= 6
      3147087.93     13884813.15      3147064.79      13884687.9
      3147050.16     13884361.65      3146997.35     13884055.15
       3147002.6     13883933.04      3146746.02     13883256.97
#Sta/Elev= 30
  4345.4   57.41  4425.4   55.51  4617.3   56.21  4756.6   55.93 4962.24   56.27
 4973.83   53.81 4975.06   52.36 4991.34   49.22 4991.69   49.82 4997.49   48.61
 4999.48   48.58 5024.85   49.68 5056.97   53.57 5085.82   55.46 5088.59   56.21
  5135.7   55.22 5186.71   55.08 5277.99    55.6  5302.7   56.61  5329.6   56.81
  5382.7   56.21  5422.7   57.01  5442.7   56.31  5482.7   56.81    5586   55.81
    5646   56.11    5656   56.71    5686   56.21  5926.3   57.81    5956   58.01
#Mann= 6 , 1 , 0
  4345.4     .14       0  4756.6      .1       0 4962.24     .04       0
 5088.59      .1       0  5329.6     .14       0  5926.3      .2       0
#XS Ineff= 2 , 0
       0    4960   55.96    5073       0   55.39
Permanent Ineff=
       F       F
Bank Sta=4962.24,5088.59
XS Rating Curve= 0
Exp/Cntr=.5,.3

Type RM Length L Ch R = 3 ,16954.1 ,,,
BEGIN DESCRIPTION:
WAYSIDE DRIVE, SKEW ANGLE OF 30 DEGREES
Structure ID:
END DESCRIPTION:
Bridge Culvert--1,0,-1,-1, 0
Deck Dist Width WeirC Skew NumUp NumDn MinLoCord MaxHiCord MaxSubmerge Is_Ogee
10,105,2.6,0, 41, 41, , , .95, 0, 1,1,,
  4345.4  4407.6  4425.4  4475.4  4617.3  4754.4 4851.39    4890 4935.19  4935.3
 4962.24 4969.26  5002.2  5023.3 5066.92 5067.03 5085.82 5088.59  5102.3 5102.41
  5112.9  5135.7  5172.3 5186.71 5208.88 5277.99  5302.7  5342.7  5377.8  5382.7
  5422.7  5442.7  5482.7  5510.3    5526    5586    5646    5656    5686  5820.3
    5956
    57.4   55.94   55.97   56.06    56.3   55.93   55.82   56.02   56.53   57.53
   57.71   57.77   58.04   58.31   58.04   58.04   57.96   57.96   57.94   56.94
   56.92   56.46   55.73    55.6   55.41    55.6   56.61   56.91   56.56    56.6
   57.01   56.64   56.81   56.35   56.35   56.34   56.35   56.71   56.35   57.11
      58
    57.4   55.92    55.5    55.6    56.2   55.92   55.81   56.02   56.18   56.18
   56.26   54.77   55.04   55.31   55.04   54.22   55.45    56.2   55.82   55.81
   55.62   55.21   55.11   55.07    55.4   55.59    56.6    56.9   56.29    56.2
      57    56.3    56.8   56.35    56.1    55.8    56.1    56.7    56.2    57.1
      58
  4345.4  4407.6  4425.4  4475.4  4617.3  4754.4 4851.39    4890 4935.19  4935.3
 4962.24 4969.26  5002.2  5023.3 5066.92 5067.03 5085.82 5088.59  5102.3 5102.41
  5112.9  5135.7  5172.3 5186.71 5208.88 5277.99  5302.7  5342.7  5377.8  5382.7
  5422.7  5442.7  5482.7  5510.3    5526    5586    5646    5656    5686  5820.3
    5956
    57.4   55.94   55.97   56.06    56.3   55.93   55.82   56.02   56.53   57.53
   57.71   57.77   58.04   58.31   58.04   58.04   57.96   57.96   57.94   56.94
   56.92   56.46   55.73    55.6   55.41    55.6   56.61   56.91   56.56    56.6
   57.01   56.64   56.81   56.35   56.35   56.34   56.35   56.71   56.35   57.11
      58
   57.24   55.76   55.34   55.44   56.04   55.76   55.65   55.86   56.02   56.02
    56.1   54.61   54.88   55.15   54.88   54.06   55.29   56.04   55.66   55.65
   55.46   55.05   54.95   54.91   55.24   55.43   56.44   56.74   56.13   56.04
   56.84   56.14   56.64   56.19   55.94   55.64   55.94   56.54   56.04   56.94
   57.84
Pier Skew, UpSta & Num, DnSta & Num=  ,4991.7, 2 ,4991.7, 2 , 0 , 0 , 0 ,,
     1.4     1.4
   48.28   55.96
     1.4     1.4
   48.12    55.8
Pier Skew, UpSta & Num, DnSta & Num=  ,5024.9, 2 ,5024.9, 2 , 0 , 0 , 0 ,,
     1.4     1.4
   48.65    56.3
     1.4     1.4
   48.49   56.14
Abutment Skew #Up #Dn= , 2 , 2
 4969.06 4973.93
   54.77   53.68
 4969.06 4973.93
   54.61   53.52
Abutment Skew #Up #Dn= , 2 , 2
 5057.07 5067.12
   53.57   55.04
 5057.07 5067.12
   53.41   54.88
BR Coef= 1 , 1 , 0 ,1.25, 0 ,,,.8,-1,2,0,
WSPro=,,,, 1 ,,,, 0 ,,,, 0 ,,,,-1 ,-1 ,-1 , 0 , 0 , 0 , 0 , 0
BR U #Sta/Elev= 81
  4345.4    57.4  4407.6   55.92  4425.4    55.5  4475.4    55.6  4617.3    56.2
  4627.3   56.18    4697   56.04  4754.4   55.92    4756   55.92  4756.6   55.92
 4801.95   55.83  4815.9   55.82 4851.39   55.81    4875   55.94    4890   56.02
 4900.15   56.07 4935.19   56.18  4935.3   56.18 4935.41   56.18  4939.2   56.19
 4962.24   56.26 4969.17   54.79 4969.26   54.77 4973.83    53.8 4973.93   53.68
 4975.06   52.35 4991.34   49.21 4991.69   49.81 4997.49    48.6 4999.48   48.57
 5000.78   48.83  5002.2   48.91 5008.66   49.25  5023.3   49.63 5024.85   49.67
 5056.97   53.56 5057.07   53.57 5066.92   54.21 5067.03   54.22 5077.59   54.91
  5077.7   54.92 5077.81   54.93 5085.82   55.45 5088.59    56.2 5099.85   55.86
 5102.19   55.82  5102.3   55.82 5102.41   55.81  5112.9   55.62  5135.7   55.21
  5172.3   55.11 5186.71   55.07 5208.88    55.4 5227.15   55.41  5233.1   55.43
 5277.99   55.59    5292   56.16  5302.7    56.6  5329.6    56.8  5342.7    56.9
  5348.9   56.79  5377.8   56.29  5382.7    56.2  5402.8    56.6  5422.7      57
  5442.7    56.3  5482.7    56.8  5492.8   56.64  5510.3   56.35    5526    56.1
  5575.3   55.85    5586    55.8    5646    56.1    5656    56.7    5686    56.2
  5690.3   56.23  5820.3    57.1  5900.3   57.63  5926.2    57.8  5926.3    57.8
    5956      58
BR U #Mann= 6
  4345.4     .14  4756.6      .1 4962.24     .04 5088.59      .1  5329.6     .14
  5926.3      .2
BR U Banks=4962.24,5088.59
BR D #Sta/Elev= 81
  4345.4   57.24  4407.6   55.76  4425.4   55.34  4475.4   55.44  4617.3   56.04
  4627.3   56.02    4697   55.88  4754.4   55.76    4756   55.76  4756.6   55.76
 4801.95   55.67  4815.9   55.66 4851.39   55.65    4875   55.78    4890   55.86
 4900.15   55.91 4935.19   56.02  4935.3   56.02 4935.41   56.02  4939.2   56.03
 4962.24    56.1 4969.17   54.63 4969.26   54.61 4973.83   53.64 4973.93   53.52
 4975.06   52.19 4991.34   49.05 4991.69   49.65 4997.49   48.44 4999.48   48.41
 5000.78   48.67  5002.2   48.75 5008.66   49.09  5023.3   49.47 5024.85   49.51
 5056.97    53.4 5057.07   53.41 5066.92   54.05 5067.03   54.06 5077.59   54.75
  5077.7   54.76 5077.81   54.77 5085.82   55.29 5088.59   56.04 5099.85    55.7
 5102.19   55.66  5102.3   55.66 5102.41   55.65  5112.9   55.46  5135.7   55.05
  5172.3   54.95 5186.71   54.91 5208.88   55.24 5227.15   55.25  5233.1   55.27
 5277.99   55.43    5292      56  5302.7   56.44  5329.6   56.64  5342.7   56.74
  5348.9   56.63  5377.8   56.13  5382.7   56.04  5402.8   56.44  5422.7   56.84
  5442.7   56.14  5482.7   56.64  5492.8   56.48  5510.3   56.19    5526   55.94
  5575.3   55.69    5586   55.64    5646   55.94    5656   56.54    5686   56.04
  5690.3   56.07  5820.3   56.94  5900.3   57.47  5926.2   57.64  5926.3   57.64
    5956   57.84
BR D #Mann= 6
  4345.4     .14  4756.6      .1 4962.24     .04 5088.59      .1  5329.6     .14
  5926.3      .2
BR D Banks=4962.24,5088.59
BC Design=,, 0 ,, 0 ,,,,,,