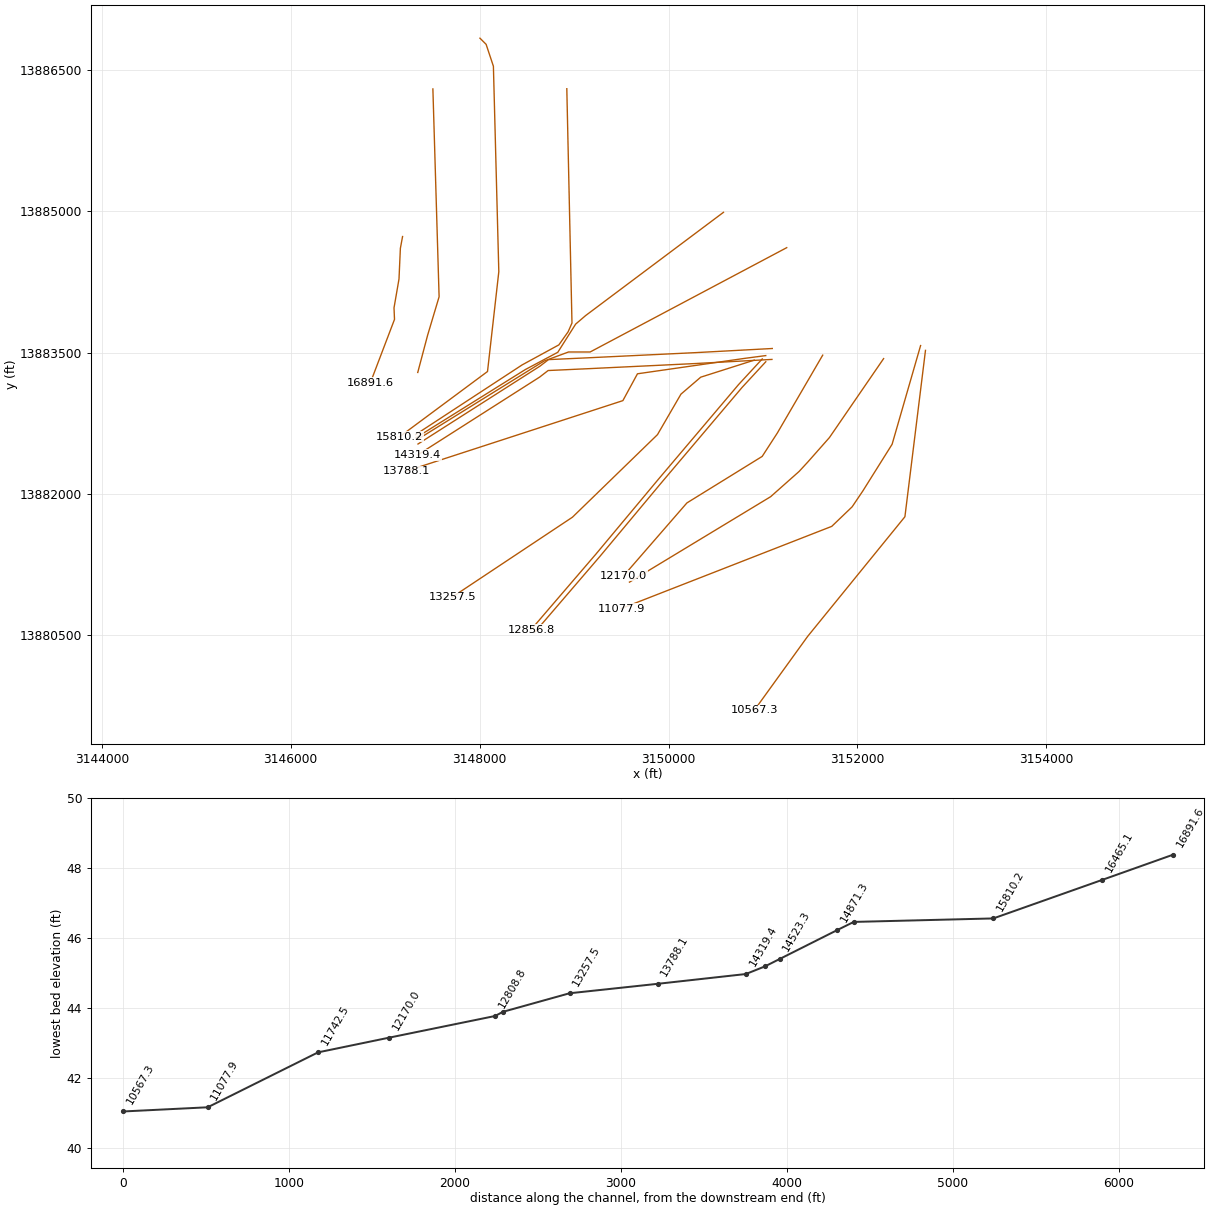
HEC-RAS study P125-00-00.PRJ: P125-00-00

--- P125-00-00.g01 (geometry) --- (continued)

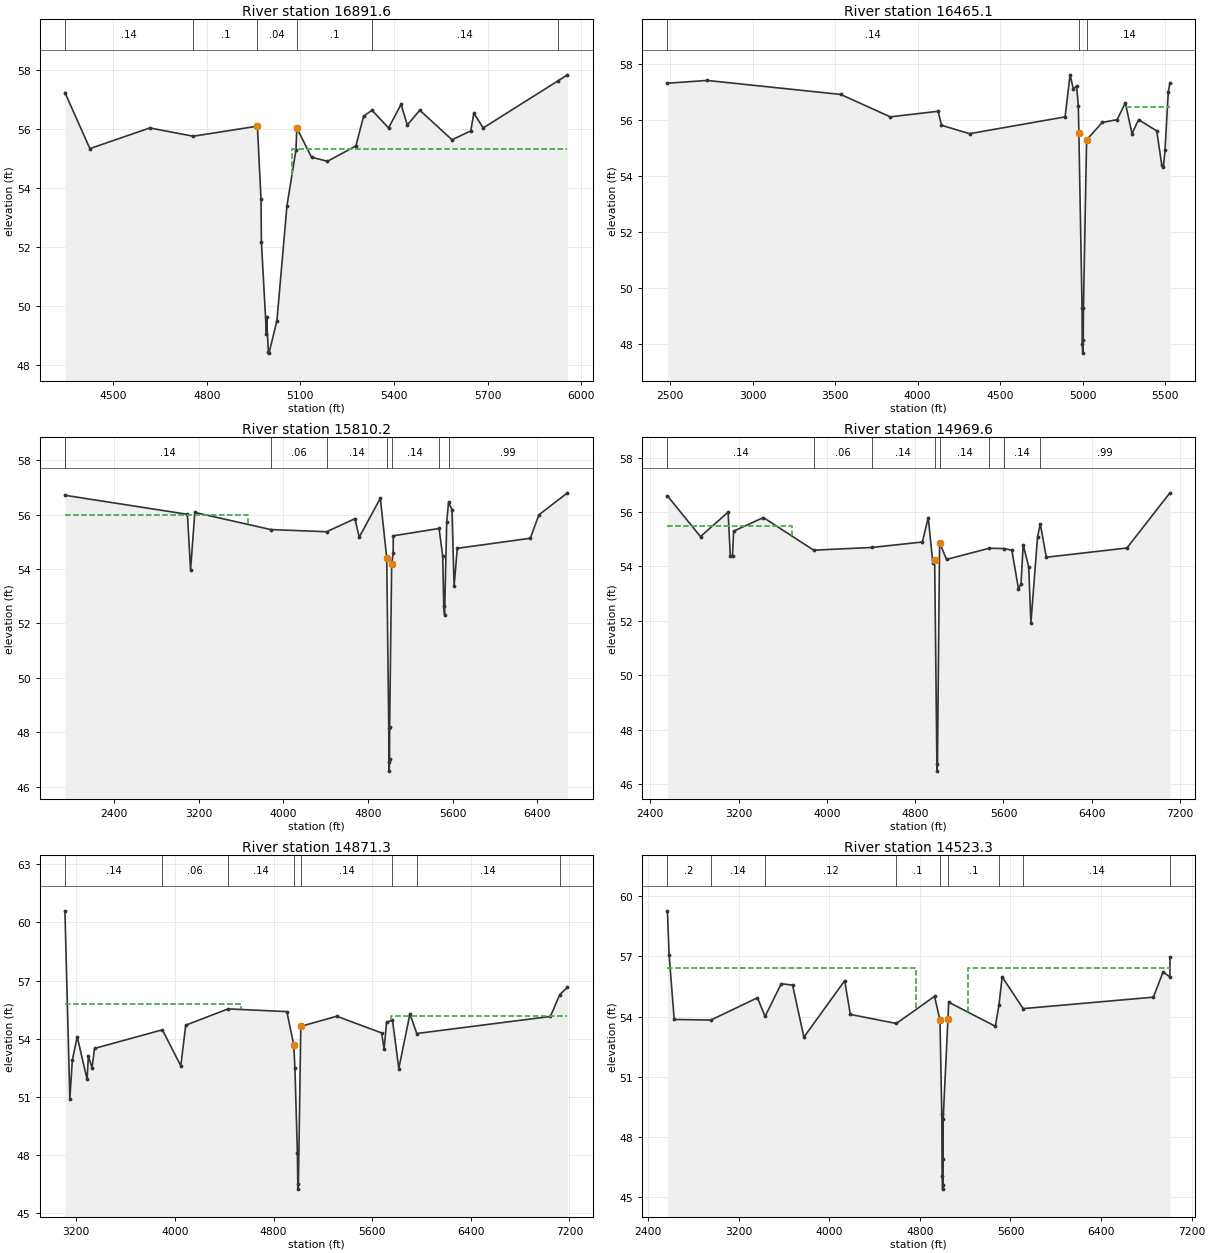
Type RM Length L Ch R = 1 ,16891.6 ,426.5,426.5,426.5
BEGIN DESCRIPTION:
Downstream Section of Bridge/Culvert/Weir
END DESCRIPTION:
XS GIS Cut Line= 6
      3147184.18     13884733.39      3147161.05     13884608.14
      3147146.42     13884281.89      3147093.61     13883975.39
      3147098.86     13883853.28      3146842.27     13883177.21
#Sta/Elev= 30
  4345.4   57.22  4425.4   55.32  4617.3   56.02  4756.6   55.74 4962.24   56.08
 4973.83   53.62 4975.06   52.17 4991.34   49.03 4991.69   49.63 4997.49   48.42
 4999.48   48.39 5024.85   49.49 5056.97   53.38 5085.82   55.27 5088.59   56.02
  5135.7   55.03 5186.71   54.89 5277.99   55.41  5302.7   56.42  5329.6   56.62
  5382.7   56.02  5422.7   56.82  5442.7   56.12  5482.7   56.62    5586   55.62
    5646   55.92    5656   56.52    5686   56.02  5926.3   57.62    5956   57.82
#Mann= 6 , 1 , 0
  4345.4     .14       0  4756.6      .1       0 4962.24     .04       0
 5088.59      .1       0  5329.6     .14       0  5926.3      .2       0
#XS Ineff= 2 , 0
       0    4960    55.9    5073       0    55.3
Permanent Ineff=
       F       F
Bank Sta=4962.24,5088.59
XS Rating Curve= 0
Exp/Cntr=.5,.3

Type RM Length L Ch R = 1 ,16465.1 ,613.8,654.9,711
BEGIN DESCRIPTION:
Cross Section 16465.1-Interpolated
END DESCRIPTION:
XS GIS Cut Line= 4
      3147505.25     13886301.18      3147571.05     13884093.32
       3147449.7     13883685.93      3147344.99     13883289.54
#Sta/Elev= 30
  2484.2    57.3  2724.2    57.4  3534.2    56.9  3834.2    56.1  4124.2    56.3
  4144.2    55.8  4314.2    55.5    4893    56.1    4923    57.6    4943    57.1
    4963    57.2    4973    56.5  4976.6   55.51  4995.8   49.27  4996.7   48.01
  4999.9   47.67    5003   48.13  5004.2   49.28  5023.3   55.28  5118.1    55.9
  5208.1      56  5258.1    56.6  5298.1    55.5  5338.1      56  5448.1    55.6
  5478.1    54.4  5488.1    54.3  5498.1    54.9  5518.1      57  5528.1    57.3
#Mann= 3 , 1 , 0
  2484.2     .14       0  4976.6     .04       0  5023.3     .14       0
#XS Ineff= 2 , 0
       0                  5263.6       0   56.45
Permanent Ineff=
       F       F
Bank Sta=4976.6,5023.3
XS Rating Curve= 0
Exp/Cntr=.3,.1

Type RM Length L Ch R = 1 ,15810.2 ,787,840.6,480.6
BEGIN DESCRIPTION:
Cross Section 15810.2
END DESCRIPTION:
XS GIS Cut Line= 6
      3148003.62     13886840.39       3148068.8     13886775.21
      3148145.96     13886542.43      3148203.32     13884359.79
      3148083.67     13883299.71      3147152.55     13882606.38
#Sta/Elev= 30
  1935.6   56.71    3093   56.01    3123   53.96    3163   56.08  3880.7   55.45
  4408.7   55.37  4676.4   55.85  4716.4   55.17  4916.4    56.6  4976.6   54.41
  4995.8   48.17  4996.7   46.91  4999.9   46.57    5003   47.03  5004.2   48.18
  5023.3   54.18  5037.1   54.57  5038.7   55.22  5471.1   55.49  5505.7   54.48
  5515.7   52.63  5523.3   52.32  5543.3   55.71  5560.6   56.45  5593.3   56.18
  5613.3   53.37  5643.3   54.76  6333.3   55.13  6414.3   55.99  6684.5    56.8
#Mann= 8 , 1 , 0
  1935.6      .2       0  1935.6     .14       0  3880.7     .06       0
  4408.7     .14       0  4976.6     .04       0  5023.3     .14       0
  5471.1      .1       0  5560.6     .99       0
#XS Ineff= 2 , 0
       0    3663      56               0
Permanent Ineff=
       F       F
Bank Sta=4976.6,5023.3
XS Rating Curve= 0
Exp/Cntr=.3,.1

Type RM Length L Ch R = 1 ,14969.6 ,160,98.3,63.2
BEGIN DESCRIPTION:
Cross Section 14969.6
END DESCRIPTION:
XS GIS Cut Line= 6
      3148923.23     13886303.62      3148977.97     13883814.74
      3148937.25     13883721.68      3148839.07      13883582.5
       3148450.5     13883370.04      3147322.01     13882629.16
#Sta/Elev= 30
  2554.7    56.6  2854.7    55.1  3104.7      56  3124.7    54.4  3144.7    54.4
  3154.7    55.3  3424.7    55.8  3880.7    54.6  4408.7    54.7  4864.7    54.9
  4918.7    55.8  4960.2   54.13  4976.7   54.22  4997.7   46.47  5001.9   46.74
  5021.4   54.87  5084.2   54.26  5471.1   54.67  5602.7   54.66  5676.1    54.6
  5736.1   53.18  5758.9   53.35  5778.9    54.8  5828.9   53.99  5848.9   51.93
  5908.9   55.08  5933.5   55.57  5988.9   54.34  6718.9   54.68  7108.9   56.71
#Mann= 8 , 1 , 0
  2554.7     .14       0  3880.7     .06       0  4408.7     .14       0
  4976.7     .04       0  5021.4     .14       0  5471.1      .1       0
  5602.7     .14       0  5933.5     .99       0
#XS Ineff= 2 , 0
       0  3684.7    55.5               0
Permanent Ineff=
       F       F
Bank Sta=4976.7,5021.4
XS Rating Curve= 0
Exp/Cntr=.3,.1

Type RM Length L Ch R = 1 ,14871.3 ,775.3,348,18.9
BEGIN DESCRIPTION:
Cross Section 14871.3-Interpolated
END DESCRIPTION:
XS GIS Cut Line= 6
      3150582.17     13884990.76      3149122.59     13883893.96
      3149016.74     13883803.11      3148827.89     13883503.91
      3148484.29     13883320.48       3147324.6     13882594.86
#Sta/Elev= 30
  3107.9    60.6  3147.9    50.9  3167.9    52.9  3207.9    54.1  3287.9    51.9
  3297.9    53.1  3327.9    52.5  3347.9    53.5  3898.4   54.46  4047.9    52.6
  4087.9    54.7  4431.9   55.54  4907.9    55.4  4963.6    53.7  4973.6    52.5
  4993.6    48.1  4997.7   46.24  5001.9   46.51  5021.4   54.64  5313.1   55.16
  5676.9    54.3  5696.9   53.46  5716.9   54.85  5765.1   54.96  5816.4   52.46
  5906.4   55.28  5962.3   54.27  7046.4   55.15    7122   56.28  7184.4   56.65
#Mann= 8 , 1 , 0
  3107.9     .14       0  3898.4     .06       0  4431.9     .14       0
  4963.6     .04       0  5021.4     .14       0  5765.1      .1       0
  5962.3     .14       0    7122      .2       0
#XS Ineff= 2 , 0
       0  4537.9    55.8  5756.9       0   55.17
Permanent Ineff=
       F       F
Bank Sta=4963.6,5021.4
XS Rating Curve= 0
Exp/Cntr=.3,.1

Type RM Length L Ch R = 1 ,14523.3 ,122.4,87.9,55.4
BEGIN DESCRIPTION:
Cross Section 14523.3-Interpolated
END DESCRIPTION:
XS GIS Cut Line= 5
      3151251.77     13884615.22      3149170.32     13883507.05
      3148941.11     13883507.05      3148680.65     13883410.11
      3147346.61     13882580.25
#Sta/Elev= 30
  2571.4   59.27  2586.4   57.08  2631.4   53.86    2955   53.83  3366.4   54.94
  3433.2   54.01  3576.4   55.64  3676.4   55.57  3776.4   52.98  4136.4   55.79
  4186.4   54.11  4592.5   53.66  4929.5   55.01  4977.6   53.83  4993.6   49.15
  4996.6   46.06  5000.9   45.41  5005.1   45.63  5005.7    46.9  5005.8   48.89
  5048.2    53.9  5054.5   54.72  5466.6   53.52  5498.6   54.59  5526.6   55.98
  5711.9    54.4  6861.6   54.97  6946.6   56.22  7007.6   55.98  7007.8   56.98
#Mann= 9 , 1 , 0
  2571.4      .2       0    2955     .14       0  3433.2     .12       0
  4592.5      .1       0  4977.6     .04       0  5048.2      .1       0
  5498.6     .12       0  5711.9     .14       0  7007.6      .2       0
#XS Ineff= 2 , 0
       0    4765    56.4  5226.6       0    56.4
Permanent Ineff=
       F       F
Bank Sta=4977.6,5048.2
XS Rating Curve= 0
Exp/Cntr=.5,.3

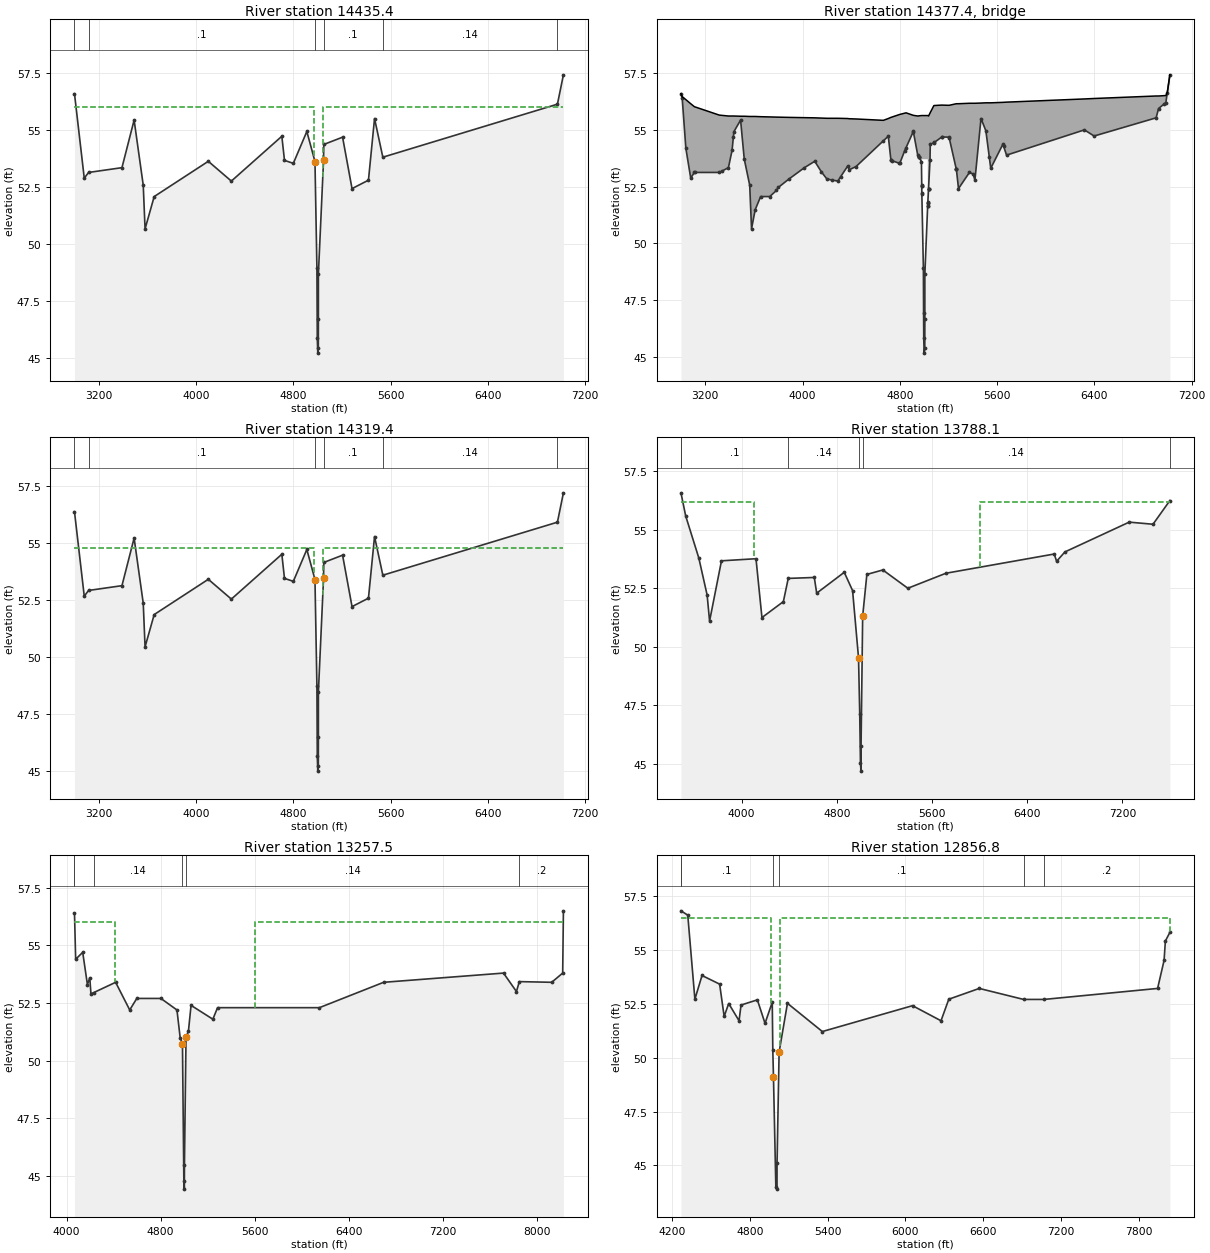
Type RM Length L Ch R = 1 ,14435.4 ,116,116,116
BEGIN DESCRIPTION:
Upstream Section of Bridge/Culvert/Weir
END DESCRIPTION:
XS GIS Cut Line= 6
      3151098.87     13883544.08      3150286.16     13883500.16
       3149147.7     13883445.31      3148729.02       13883426.
      3148639.15     13883356.57      3147347.56     13882529.46
#Sta/Elev= 30
  3000.3    56.6  3080.6   52.89  3116.3   53.14  3390.6   53.35  3490.6   55.44
  3565.6   52.58  3580.6   50.66  3655.6   52.08  4100.6   53.63  4290.1   52.76
  4705.1   54.73    4727   53.67  4799.7   53.54  4910.8   54.94  4977.6   53.62
  4993.6   48.94  4996.6   45.85  5000.9    45.2  5005.1   45.42  5005.7   46.69
  5005.8   48.68  5048.2   53.69  5050.1   54.37  5204.6   54.69  5282.3   52.43
  5417.4    52.8  5467.4   55.51  5535.6   53.81  6971.2   56.14  7020.4   57.43
#Mann= 6 , 1 , 0
  3000.3      .2       0  3116.3      .1       0  4977.6     .04       0
  5048.2      .1       0  5535.6     .14       0  6971.2      .2       0
#XS Ineff= 2 , 0
       0    4970      56    5042       0      56
Permanent Ineff=
       F       F
Bank Sta=4977.6,5048.2
XS Rating Curve= 0
Exp/Cntr=.5,.3

Type RM Length L Ch R = 3 ,14377.4 ,,,
BEGIN DESCRIPTION:
LITTLE YORK ROAD
Structure ID: P25-05
END DESCRIPTION:
Bridge Culvert--1,0,-1,-1, 0
Deck Dist Width WeirC Skew NumUp NumDn MinLoCord MaxHiCord MaxSubmerge Is_Ogee
10,96,2.6,0, 59, 59, , , .95, 0, 1,1,,
  3000.3  3010.6  3040.6  3080.6  3110.6  3315.6  3390.6  3420.6  3435.6  3490.6
  3520.6  3565.6  3580.6  3610.6  3655.6  3730.6  3800.6  3885.6  4100.6  4200.6
  4290.1  4370.1  4385.1  4440.1  4664.6  4705.1    4727  4799.7  4851.2  4910.8
  4947.2  4977.6 4980.11  4980.2 5029.99  5030.1 5036.11  5048.2  5050.1  5079.9
  5144.4  5204.6  5264.3  5282.3  5372.3  5402.3  5417.4  5467.4  5507.4  5547.4
  5647.4  5677.4  6317.4  6397.4  6907.4  6927.4  6987.4  6999.2  7020.4
   56.58   56.45   56.32   56.14   56.01   55.64    55.6    55.6    55.6   55.59
   55.59   55.58   55.58   55.58   55.57   55.56   55.55   55.54   55.52    55.5
    55.5   55.49   55.48   55.47   55.41   55.49   55.54   55.67   55.74   55.63
    55.6   55.62   55.62   55.62   55.62   55.62    55.6   55.73   55.75   56.06
   56.08   56.07   56.14   56.14   56.16   56.16   56.16   56.17   56.18   56.18
    56.2   56.21   56.35   56.37   56.48   56.48    56.5   56.63   57.41
   56.58   56.38   54.18   52.87   53.12   53.12   53.33   54.09   54.91   55.42
   53.71   52.56   50.64   51.48   52.06   52.06   52.46   52.82   53.61   52.83
   52.74   53.39   53.24   53.38   54.51   54.71   53.65   53.52   54.21   54.92
   53.88    53.6   52.54    53.7    53.7   51.78   52.41   53.67   54.35   54.43
   54.68   54.67   53.29   52.41   53.12   53.05   52.78   55.49   54.95    53.3
   54.36   53.88   54.99   54.72   55.52   55.93   56.19   56.63   57.41
  3000.3  3010.6  3040.6  3080.6  3110.6  3315.6  3390.6  3420.6  3435.6  3490.6
  3520.6  3565.6  3580.6  3610.6  3655.6  3730.6  3800.6  3885.6  4100.6  4200.6
  4290.1  4370.1  4385.1  4440.1  4664.6  4705.1    4727  4799.7  4851.2  4910.8
  4947.2  4977.6 4980.11  4980.2 5029.99  5030.1 5036.11  5048.2  5050.1  5079.9
  5144.4  5204.6  5264.3  5282.3  5372.3  5402.3  5417.4  5467.4  5507.4  5547.4
  5647.4  5677.4  6317.4  6397.4  6907.4  6927.4  6987.4  6999.2  7020.4
    56.5   56.45   56.32   56.14   56.01   55.64    55.6    55.6    55.6   55.59
   55.59   55.58   55.58   55.58   55.57   55.56   55.55   55.54   55.52    55.5
    55.5   55.49   55.48   55.47   55.41   55.49   55.54   55.67   55.74   55.63
    55.6   55.62   55.62   55.62   55.62   55.62    55.6   55.73   55.75   56.06
   56.08   56.07   56.14   56.14   56.16   56.16   56.16   56.17   56.18   56.18
    56.2   56.21   56.35   56.37   56.48   56.48    56.5   56.56   57.33
   56.38   56.18   53.98   52.67   52.92   52.92   53.13   53.89   54.71   55.22
   53.51   52.36   50.44   51.28   51.86   51.86   52.26   52.62   53.41   52.63
   52.54   53.19   53.04   53.18   54.31   54.51   53.45   53.32   54.01   54.72
   53.68    53.4   52.34    53.5    53.5   51.58   52.21   53.47   54.15   54.23
   54.48   54.47   53.09   52.21   52.92   52.85   52.58   55.29   54.75    53.1
   54.16   53.68   54.79   54.52   55.32   55.73   55.99   56.43   57.21
Abutment Skew #Up #Dn= , 2 , 2
    4980    4981
    53.7   52.17
    4980    4981
    53.5   51.97
Abutment Skew #Up #Dn= , 2 , 2
  5028.9 5030.19
   51.66    53.7
  5028.9 5030.19
   51.46    53.5
BR Coef= 1 , 1 , 0 ,1.25, 0 ,,,.8,0,2,0,
WSPro=,,,, 1 ,,,, 0 ,,,, 0 ,,,,-1 ,-1 ,-1 , 0 , 0 , 0 , 0 , 0
BR U #Sta/Elev= 98
  3000.3   56.58  3010.6   56.38  3040.6   54.18  3080.6   52.87  3110.6   53.12
  3116.3   53.12  3315.6   53.12  3341.3   53.19  3390.6   53.33  3420.6   54.09
  3431.3   54.67  3435.6   54.91  3490.6   55.42  3520.6   53.71  3565.6   52.56
  3580.6   50.64  3610.6   51.48  3655.6   52.06  3730.6   52.06  3785.6   52.33
  3800.6   52.46  3885.6   52.82  4015.6   53.33  4100.6   53.61  4155.6   53.14
  4200.6   52.83  4239.2   52.79  4290.1   52.74  4314.2   52.94  4370.1   53.39
  4385.1   53.24  4440.1   53.38  4664.6   54.51  4705.1   54.71  4726.8   53.66
    4727   53.65  4733.2   53.64  4792.3   53.53  4799.7   53.52  4840.4   54.08
  4851.2   54.21  4909.4    54.9  4910.8   54.92  4947.2   53.88 4955.69    53.8
  4955.8    53.8 4955.91    53.8  4977.6    53.6    4980   52.59 4980.11   52.54
  4980.2   52.51  4980.9   52.21    4981   52.17  4993.6   48.92  4995.3   46.96
  4996.6   45.83  5000.9   45.18  5005.1    45.4  5005.7   46.67  5005.8   48.66
  5028.8   51.65  5028.9   51.66 5029.99   51.77  5030.1   51.78  5030.2    51.8
 5035.89   52.39    5036    52.4 5036.11   52.41  5048.2   53.67  5050.1   54.35
  5079.9   54.43  5083.9   54.44  5143.1   54.67  5144.4   54.68  5204.6   54.67
  5206.3   54.63  5263.9   53.27  5264.3   53.29  5264.9   53.26  5282.3   52.41
  5372.3   53.12  5402.3   53.05  5417.4   52.78  5467.4   55.49  5507.4   54.95
  5535.6   53.79  5547.4    53.3  5647.4   54.36  5653.2   54.27  5677.4   53.88
  6317.4   54.99  6397.4   54.72  6907.4   55.52  6927.4   55.93  6971.2   56.12
  6987.4   56.19  6999.2   56.63  7020.4   57.41
BR U #Mann= 6
  3000.3      .2  3116.3      .1  4977.6     .04  5048.2      .1  5535.6     .14
  6971.2      .2
BR U Banks=4977.6,5048.2
BR D #Sta/Elev= 98
  3000.3   56.38  3010.6   56.18  3040.6   53.98  3080.6   52.67  3110.6   52.92
  3116.3   52.92  3315.6   52.92  3341.3   52.99  3390.6   53.13  3420.6   53.89
  3431.3   54.47  3435.6   54.71  3490.6   55.22  3520.6   53.51  3565.6   52.36
  3580.6   50.44  3610.6   51.28  3655.6   51.86  3730.6   51.86  3785.6   52.13
  3800.6   52.26  3885.6   52.62  4015.6   53.13  4100.6   53.41  4155.6   52.94
  4200.6   52.63  4239.2   52.59  4290.1   52.54  4314.2   52.74  4370.1   53.19
  4385.1   53.04  4440.1   53.18  4664.6   54.31  4705.1   54.51  4726.8   53.46
    4727   53.45  4733.2   53.44  4792.3   53.33  4799.7   53.32  4840.4   53.88
  4851.2   54.01  4909.4    54.7  4910.8   54.72  4947.2   53.68 4955.69    53.6
  4955.8    53.6 4955.91    53.6  4977.6    53.4    4980   52.39 4980.11   52.34
  4980.2   52.31  4980.9   52.01    4981   51.97  4993.6   48.72  4995.3   46.76
  4996.6   45.63  5000.9   44.98  5005.1    45.2  5005.7   46.47  5005.8   48.46
  5028.8   51.45  5028.9   51.46 5029.99   51.57  5030.1   51.58  5030.2    51.6
 5035.89   52.19    5036    52.2 5036.11   52.21  5048.2   53.47  5050.1   54.15
  5079.9   54.23  5083.9   54.24  5143.1   54.47  5144.4   54.48  5204.6   54.47
  5206.3   54.43  5263.9   53.07  5264.3   53.09  5264.9   53.06  5282.3   52.21
  5372.3   52.92  5402.3   52.85  5417.4   52.58  5467.4   55.29  5507.4   54.75
  5535.6   53.59  5547.4    53.1  5647.4   54.16  5653.2   54.07  5677.4   53.68
  6317.4   54.79  6397.4   54.52  6907.4   55.32  6927.4   55.73  6971.2   55.92
  6987.4   55.99  6999.2   56.43  7020.4   57.21
BR D #Mann= 6
  3000.3      .2  3116.3      .1  4977.6     .04  5048.2      .1  5535.6     .14
  6971.2      .2
BR D Banks=4977.6,5048.2
BC Design=,, 0 ,, 0 ,,,,,,

Type RM Length L Ch R = 1 ,14319.4 ,531.3,531.3,531.3
BEGIN DESCRIPTION:
Downstream Section of Bridge/Culvert/Weir
END DESCRIPTION:
XS GIS Cut Line= 6
      3151095.46     13883428.13      3150282.74     13883384.22
      3149144.28     13883329.37       3148725.6     13883310.06
      3148635.73     13883240.63      3147344.15     13882413.51
#Sta/Elev= 30
  3000.3   56.38  3080.6   52.67  3116.3   52.92  3390.6   53.13  3490.6   55.22
  3565.6   52.36  3580.6   50.44  3655.6   51.86  4100.6   53.41  4290.1   52.54
  4705.1   54.51    4727   53.45  4799.7   53.32  4910.8   54.72  4977.6    53.4
  4993.6   48.72  4996.6   45.63  5000.9   44.98  5005.1    45.2  5005.7   46.47
  5005.8   48.46  5048.2   53.47  5050.1   54.15  5204.6   54.47  5282.3   52.21
  5417.4   52.58  5467.4   55.29  5535.6   53.59  6971.2   55.92  7020.4   57.21
#Mann= 6 , 1 , 0
  3000.3      .2       0  3116.3      .1       0  4977.6     .04       0
  5048.2      .1       0  5535.6     .14       0  6971.2      .2       0
#XS Ineff= 2 , 0
       0    4970    54.8    5042       0    54.8
Permanent Ineff=
       F       F
Bank Sta=4977.6,5048.2
XS Rating Curve= 0
Exp/Cntr=.5,.3

Type RM Length L Ch R = 1 ,13788.1 ,338.6,530.6,760.3
BEGIN DESCRIPTION:
Cross Section 13788.1-Interpolated
END DESCRIPTION:
XS GIS Cut Line= 5
      3151029.73     13883468.77      3150801.25     13883438.53
      3149671.32     13883275.44      3149516.88     13882990.33
      3147224.13     13882241.92
#Sta/Elev= 30
    3490   56.57    3530   55.58    3640   53.79    3710   52.21  3730.5    51.1
  3830.5   53.67  4120.5   53.76  4170.5   51.25  4350.5   51.93  4391.5   52.92
  4610.5   52.96  4630.5   52.29  4862.1   53.18  4932.1    52.4  4982.1   49.53
  4992.1   47.15  4998.2   45.05  5002.5    44.7  5003.3   45.76  5016.8   51.31
  5052.1   53.09  5186.4   53.28  5396.4    52.5  5716.4   53.14  6626.4   53.96
  6646.4   53.65  6716.4   54.05  7256.4   55.32  7456.4   55.23  7598.2   56.24
#Mann= 6 , 1 , 0
    3490      .2       0    3490      .1       0  4391.5     .14       0
  4982.1     .04       0  5016.8     .14       0  7598.2      .2       0
#XS Ineff= 2 , 0
       0    4100    56.2    6000       0    56.2
Permanent Ineff=
       F       F
Bank Sta=4982.1,5016.8
XS Rating Curve= 0
Exp/Cntr=.3,.1

Type RM Length L Ch R = 1 ,13257.5 ,360.6,400.7,419.1
BEGIN DESCRIPTION:
Cross Section 13257.5
END DESCRIPTION:
XS GIS Cut Line= 6
      3150908.35     13883420.41      3150341.06     13883239.42
      3150131.69     13883059.13      3149883.02     13882628.85
      3148982.96     13881752.11       3147710.2     13880903.59
#Sta/Elev= 30
  4067.7    56.4  4077.7    54.4  4137.7    54.7  4177.7    53.3  4197.7    53.6
  4207.7    52.9  4229.8   52.95  4417.7    53.4  4537.7    52.2  4597.7    52.7
  4803.2    52.7  4939.5    52.2  4966.8      51  4986.4   50.73  4998.2   44.78
  5002.5   44.43  5003.3   45.49  5016.8   51.04    5037   51.27  5059.5    52.4
    5245    51.8    5285    52.3  6151.5    52.3    6698    53.4    7718    53.8
    7828      53  7852.8   53.43    8128    53.4  8221.5    53.8  8227.7    56.5
#Mann= 6 , 1 , 0
  4067.7      .2       0  4067.7      .1       0  4229.8     .14       0
  4986.4     .04       0  5016.8     .14       0  7852.8      .2       0
#XS Ineff= 2 , 0
       0    4415      56    5600       0      56
Permanent Ineff=
       F       F
Bank Sta=4986.4,5016.8
XS Rating Curve= 0
Exp/Cntr=.5,.3

Type RM Length L Ch R = 1 ,12856.8 ,48,48,48
BEGIN DESCRIPTION:
Upstream Section of Bridge/Culvert/Weir
END DESCRIPTION:
XS GIS Cut Line= 5
      3150992.52     13883433.22      3150741.94     13883161.03
      3149889.87     13882151.47      3149233.63      13881362.6
       3148545.8     13880558.78
#Sta/Elev= 30
  4266.5   56.81  4319.1   56.61  4374.1   52.71  4429.1   53.81  4565.1   53.41
  4600.1   51.91  4635.1   52.51  4715.1   51.71  4730.4   52.44  4856.5   52.68
  4915.7   51.59  4971.5   52.57  4975.7   50.36  4980.8   49.11  4999.2   43.99
  5008.2    43.9  5008.5   45.09  5024.3   50.25  5088.7   52.52  5358.1   51.21
  6054.5   52.41  6274.5   51.71  6334.5   52.71  6569.8   53.21    6912    52.7
  7069.9    52.7  7946.8   53.21  7996.8   54.51  8006.8   55.41  8041.6   55.81
#Mann= 6 , 1 , 0
  4266.5      .2       0  4266.5      .1       0  4980.8    .042       0
  5024.3      .1       0    6912     .14       0  7069.9      .2       0
#XS Ineff= 2 , 0
       0    4964    56.5    5032       0    56.5
Permanent Ineff=
       F       F
Bank Sta=4980.8,5024.3
XS Rating Curve= 0
Exp/Cntr=.5,.3

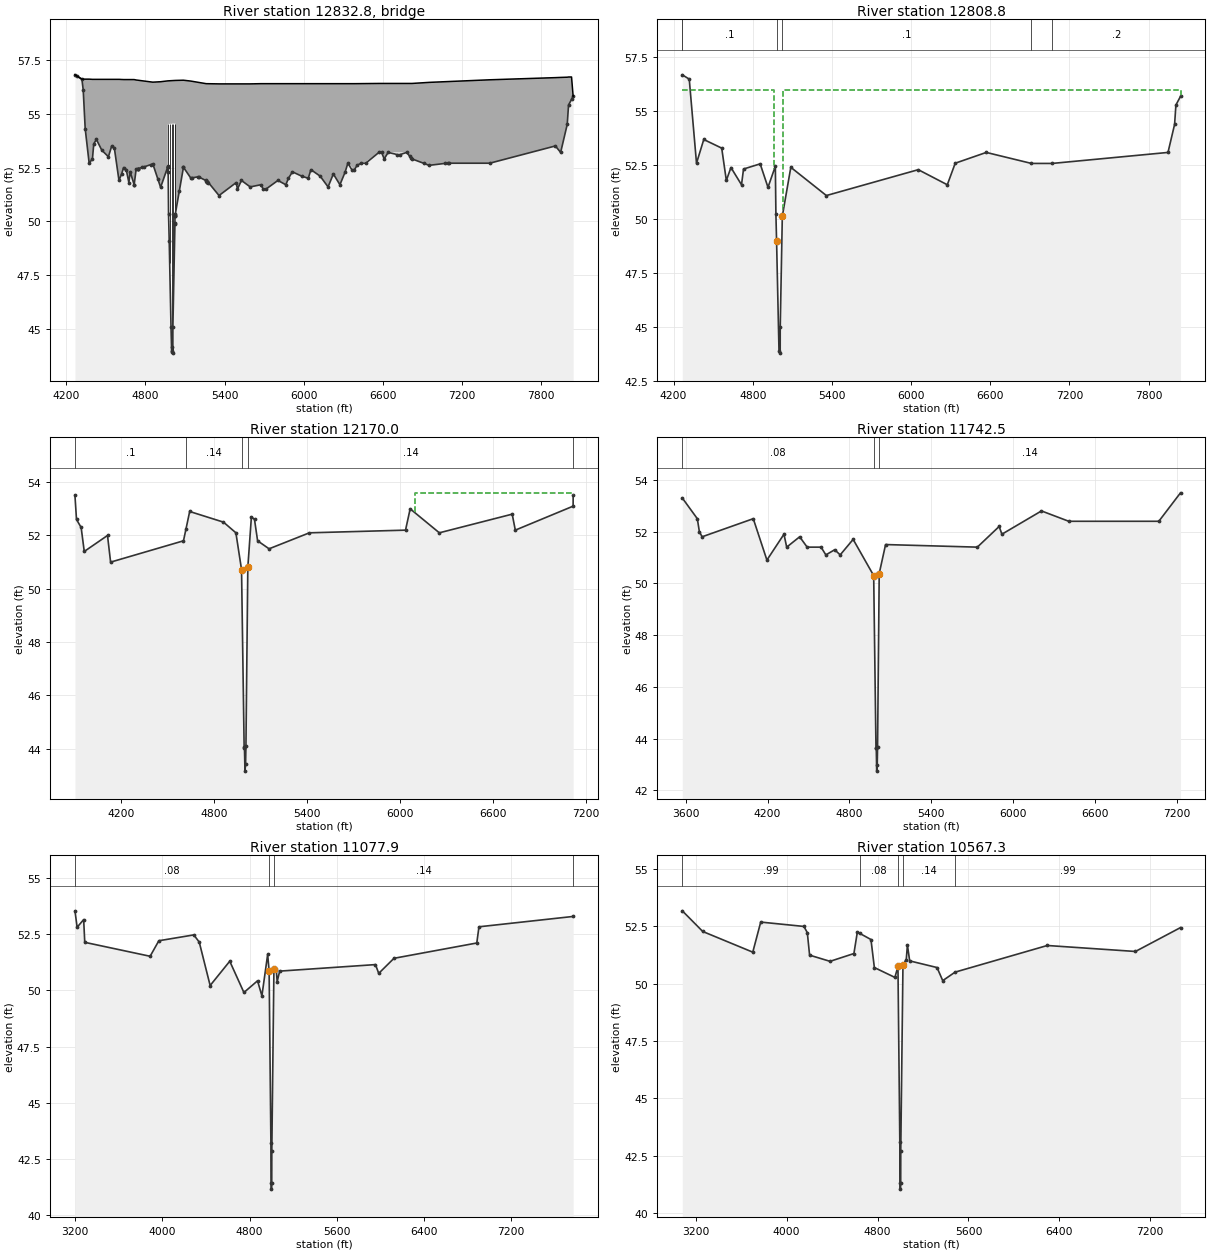
Type RM Length L Ch R = 3 ,12832.8 ,,,
BEGIN DESCRIPTION:
UNION PACIFIC RAILROAD
Structure ID:
END DESCRIPTION:
Bridge Culvert--1,0,-1,-1, 0
Deck Dist Width WeirC Skew NumUp NumDn MinLoCord MaxHiCord MaxSubmerge Is_Ogee
10,28,2.6,0, 60, 60, , , .95, 0, 1,1,,
  4266.5  4319.1  4329.1  4344.1  4374.1  4399.1  4409.1  4429.1  4470.1  4520.1
  4545.1  4565.1  4600.1  4635.1  4655.1  4675.1  4685.1  4715.1  4730.4  4856.5
  4915.7 4970.41  4970.5 5026.59  5026.7  5088.7  5144.3  5260.7  5358.1  5488.1
  5498.1  5528.1  5594.5  5674.5  5714.5  5804.5  5864.5  5914.5  6034.5  6054.5
  6124.5  6184.5  6224.5  6274.5  6334.5  6384.5  6569.8  6589.8  6609.8  6639.8
  6779.8  6819.8  6949.8  7409.8  7906.8  7946.8  7996.8  8006.8  8029.5  8041.6
    56.8    56.6    56.6    56.6    56.6   56.59   56.59   56.59   56.59   56.59
   56.59   56.59   56.59   56.58   56.58   56.58   56.58   56.58   56.56   56.46
   56.48   56.52   56.52   56.54   56.54   56.55   56.51   56.39   56.38   56.38
   56.38   56.38   56.38   56.39   56.39   56.39   56.39   56.39   56.39   56.39
   56.39   56.39   56.39   56.39   56.39   56.39    56.4    56.4    56.4    56.4
    56.4    56.4   56.45   56.57   56.67   56.68   56.69    56.7    56.7    55.8
    56.8    56.6    56.1    54.3    52.7    52.9    53.6    53.8    53.3      53
    53.5    53.4    51.9    52.5    52.4    51.8    52.3    51.7   52.43   52.67
   51.58   52.54   54.52   54.54   50.33   52.51   52.01    51.9    51.2    51.8
    51.5    51.9    51.6    51.7    51.5    51.9    51.7    52.3      52    52.4
    52.1    51.6    52.2    51.7    52.7    52.4    53.2    53.2    52.9    53.2
    53.2    52.9    52.6    52.7    53.5    53.2    54.5    55.4   55.66    55.8
  4266.5  4319.1  4329.1  4344.1  4374.1  4399.1  4409.1  4429.1  4470.1  4520.1
  4545.1  4565.1  4600.1  4635.1  4655.1  4675.1  4685.1  4715.1  4730.4  4856.5
  4915.7 4970.41  4970.5 5026.59  5026.7  5088.7  5144.3  5260.7  5358.1  5488.1
  5498.1  5528.1  5594.5  5674.5  5714.5  5804.5  5864.5  5914.5  6034.5  6054.5
  6124.5  6184.5  6224.5  6274.5  6334.5  6384.5  6569.8  6589.8  6609.8  6639.8
  6779.8  6819.8  6949.8  7409.8  7906.8  7946.8  7996.8  8006.8  8029.5  8041.6
    56.8    56.6    56.6    56.6    56.6   56.59   56.59   56.59   56.59   56.59
   56.59   56.59   56.59   56.58   56.58   56.58   56.58   56.58   56.56   56.46
   56.48   56.52   56.52   56.54   56.54   56.55   56.51   56.39   56.38   56.38
   56.38   56.38   56.38   56.39   56.39   56.39   56.39   56.39   56.39   56.39
   56.39   56.39   56.39   56.39   56.39   56.39    56.4    56.4    56.4    56.4
    56.4    56.4   56.45   56.57   56.67   56.68   56.69    56.7    56.7    55.8
    56.7    56.5      56    54.2    52.6    52.8    53.5    53.7    53.2    52.9
    53.4    53.3    51.8    52.4    52.3    51.7    52.2    51.6   52.33   52.57
   51.48   52.44   54.42   54.44   50.23   52.41   51.91    51.8    51.1    51.7
    51.4    51.8    51.5    51.6    51.4    51.8    51.6    52.2    51.9    52.3
      52    51.5    52.1    51.6    52.6    52.3    53.1    53.1    52.8    53.1
    53.1    52.8    52.5    52.6    53.4    53.1    54.4    55.3   55.56    55.7
Pier Skew, UpSta & Num, DnSta & Num=  ,4971.5, 2 ,4971.5, 2 , 0 , 0 , 0 ,,
       1       1
   51.46   55.52
       1       1
   51.36   55.42
Pier Skew, UpSta & Num, DnSta & Num=  ,4984.3, 2 ,4984.3, 2 , 0 , 0 , 0 ,,
       1       1
   46.93   55.52
       1       1
   46.83   55.42
Pier Skew, UpSta & Num, DnSta & Num=  ,4999.2, 2 ,4999.2, 2 , 0 , 0 , 0 ,,
       1       1
   42.96   55.53
       1       1
   42.86   55.43
Pier Skew, UpSta & Num, DnSta & Num=  ,5011.6, 2 ,5011.6, 2 , 0 , 0 , 0 ,,
       1       1
   44.88   55.53
       1       1
   44.78   55.43
Pier Skew, UpSta & Num, DnSta & Num=  ,5025.5, 2 ,5025.5, 2 , 0 , 0 , 0 ,,
       1       1
   49.26   55.54
       1       1
   49.16   55.44
Abutment Skew #Up #Dn= , 2 , 2
  4970.3    4973
   54.52   52.27
  4970.3    4973
   54.42   52.17
Abutment Skew #Up #Dn= , 2 , 2
  5024.2 5026.79
   49.92   54.54
  5024.2 5026.79
   49.82   54.44
BR Coef= 1 , 1 , 0 ,1.25, 0 ,,,.8,0,2,0,
WSPro=,,,, 1 ,,,, 0 ,,,, 0 ,,,,-1 ,-1 ,-1 , 0 , 0 , 0 , 0 , 0
BR U #Sta/Elev= 113
  4266.5    56.8  4281.5   56.74  4319.1    56.6  4329.1    56.1  4344.1    54.3
  4374.1    52.7  4399.1    52.9  4409.1    53.6  4429.1    53.8  4470.1    53.3
  4520.1      53  4545.1    53.5  4565.1    53.4  4600.1    51.9  4620.1    52.2
  4635.1    52.5  4655.1    52.4  4675.1    51.8  4685.1    52.3  4715.1    51.7
  4715.4   51.71  4730.4   52.43 4745.09   52.45  4745.2   52.45 4745.31   52.45
  4777.7   52.51  4790.3   52.53  4839.1   52.63  4856.5   52.67    4895   51.96
  4915.7   51.58  4970.3   52.54 4970.41   52.54  4970.5   52.54  4971.5   52.56
  4972.9   52.29    4973   52.27  4975.7   50.35  4980.8    49.1  4994.5   45.09
  4999.2   43.98  4999.6   43.96  5004.5   44.19  5008.2   43.89  5008.5   45.08
  5024.1   49.89  5024.2   49.92  5024.3   50.24  5024.6   50.25 5026.59   50.32
  5026.7   50.33  5057.3   51.41  5088.7   52.51  5088.8   52.51  5144.3   52.01
  5152.2   52.02    5202   52.07  5208.6   52.05  5260.6   51.89  5260.7    51.9
 5268.69   51.85  5268.8   51.85 5268.91   51.85    5269   51.85  5278.1    51.8
  5358.1    51.2  5488.1    51.8  5498.1    51.5  5528.1    51.9  5594.5    51.6
  5674.5    51.7  5694.5    51.5  5714.5    51.5  5804.5    51.9  5864.5    51.7
  5884.5      52  5914.5    52.3  5984.5    52.1  6034.5      52  6054.5    52.4
  6124.5    52.1  6184.5    51.6  6224.5    52.2  6274.5    51.7  6314.5    52.3
  6334.5    52.7  6364.5    52.4  6384.5    52.4  6404.5    52.6  6434.5    52.7
  6469.8    52.7  6569.8    53.2  6589.8    53.2  6609.8    52.9  6639.8    53.2
  6709.8    53.1  6729.8    53.1  6779.8    53.2  6802.5   53.03  6812.5   52.95
  6819.8    52.9    6912   52.69  6949.8    52.6  7069.9   52.69  7089.8    52.7
  7099.5    52.7  7409.8    52.7  7906.8    53.5  7946.8    53.2  7996.8    54.5
  8006.8    55.4  8029.5   55.66  8041.6    55.8
BR U #Mann= 6
  4266.5      .2  4266.5      .1  4980.8    .042  5024.3      .1    6912     .14
  7069.9      .2
BR U Banks=4980.8,5024.3
BR D #Sta/Elev= 113
  4266.5    56.7  4281.5   56.64  4319.1    56.5  4329.1      56  4344.1    54.2
  4374.1    52.6  4399.1    52.8  4409.1    53.5  4429.1    53.7  4470.1    53.2
  4520.1    52.9  4545.1    53.4  4565.1    53.3  4600.1    51.8  4620.1    52.1
  4635.1    52.4  4655.1    52.3  4675.1    51.7  4685.1    52.2  4715.1    51.6
  4715.4   51.61  4730.4   52.33 4745.09   52.35  4745.2   52.35 4745.31   52.35
  4777.7   52.41  4790.3   52.43  4839.1   52.53  4856.5   52.57    4895   51.86
  4915.7   51.48  4970.3   52.44 4970.41   52.44  4970.5   52.44  4971.5   52.46
  4972.9   52.19    4973   52.17  4975.7   50.25  4980.8      49  4994.5   44.99
  4999.2   43.88  4999.6   43.86  5004.5   44.09  5008.2   43.79  5008.5   44.98
  5024.1   49.79  5024.2   49.82  5024.3   50.14  5024.6   50.15 5026.59   50.22
  5026.7   50.23  5057.3   51.31  5088.7   52.41  5088.8   52.41  5144.3   51.91
  5152.2   51.92    5202   51.97  5208.6   51.95  5260.6   51.79  5260.7    51.8
 5268.69   51.75  5268.8   51.75 5268.91   51.75    5269   51.75  5278.1    51.7
  5358.1    51.1  5488.1    51.7  5498.1    51.4  5528.1    51.8  5594.5    51.5
  5674.5    51.6  5694.5    51.4  5714.5    51.4  5804.5    51.8  5864.5    51.6
  5884.5    51.9  5914.5    52.2  5984.5      52  6034.5    51.9  6054.5    52.3
  6124.5      52  6184.5    51.5  6224.5    52.1  6274.5    51.6  6314.5    52.2
  6334.5    52.6  6364.5    52.3  6384.5    52.3  6404.5    52.5  6434.5    52.6
  6469.8    52.6  6569.8    53.1  6589.8    53.1  6609.8    52.8  6639.8    53.1
  6709.8      53  6729.8      53  6779.8    53.1  6802.5   52.93  6812.5   52.85
  6819.8    52.8    6912   52.59  6949.8    52.5  7069.9   52.59  7089.8    52.6
  7099.5    52.6  7409.8    52.6  7906.8    53.4  7946.8    53.1  7996.8    54.4
  8006.8    55.3  8029.5   55.56  8041.6    55.7
BR D #Mann= 6
  4266.5      .2  4266.5      .1  4980.8    .042  5024.3      .1    6912     .14
  7069.9      .2
BR D Banks=4980.8,5024.3
BC Design=,, 0 ,, 0 ,,,,,,

Type RM Length L Ch R = 1 ,12808.8 ,638.8,638.8,638.8
BEGIN DESCRIPTION:
Downstream Section of Bridge/Culvert/Weir
END DESCRIPTION:
XS GIS Cut Line= 5
       3151030.1     13883403.34      3150779.52     13883131.15
      3149927.45     13882121.59      3149271.21     13881332.72
      3148583.38     13880528.91
#Sta/Elev= 30
  4266.5   56.69  4319.1   56.49  4374.1   52.59  4429.1   53.69  4565.1   53.29
  4600.1   51.79  4635.1   52.39  4715.1   51.59  4730.4   52.32  4856.5   52.56
  4915.7   51.47  4971.5   52.45  4975.7   50.24  4980.8   48.99  4999.2   43.87
  5008.2   43.78  5008.5   44.97  5024.3   50.13  5088.7    52.4  5358.1   51.09
  6054.5   52.29  6274.5   51.59  6334.5   52.59  6569.8   53.09    6912   52.58
  7069.9   52.58  7946.8   53.09  7996.8   54.39  8006.8   55.29  8041.6   55.69
#Mann= 6 , 1 , 0
  4266.5      .2       0  4266.5      .1       0  4980.8    .042       0
  5024.3      .1       0    6912     .14       0  7069.9      .2       0
#XS Ineff= 2 , 0
       0    4964      56    5032       0      56
Permanent Ineff=
       F       F
Bank Sta=4980.8,5024.3
XS Rating Curve= 0
Exp/Cntr=.5,.3

Type RM Length L Ch R = 1 ,12170.0 ,511.7,427.5,424.5
BEGIN DESCRIPTION:
Cross Section 12170.0-Interpolated
END DESCRIPTION:
XS GIS Cut Line= 5
      3151632.78     13883473.49      3151151.49     13882645.03
      3150992.04     13882397.88      3150194.79     13881903.58
       3149525.1     13881130.25
#Sta/Elev= 30
  3902.9    53.5  3912.9    52.6  3942.9    52.3  3962.9    51.4  4112.9      52
  4132.9      51  4602.9    51.8  4618.6   52.23  4642.9    52.9    4861    52.5
    4941    52.1  4977.4   50.72  4994.2   44.05  4996.3   44.04  4999.5   43.16
  5003.4   43.41  5005.8    44.1  5017.9    50.8    5041    52.7    5061    52.6
    5081    51.8  5155.1    51.5  5415.1    52.1  6035.1    52.2  6065.1      53
  6253.2    52.1  6723.2    52.8  6743.2    52.2  7116.2    53.1  7116.3    53.5
#Mann= 5 , 1 , 0
  3902.9      .1       0  4618.6     .14       0  4977.4     .04       0
  5017.9     .14       0  7116.2      .2       0
#XS Ineff= 2 , 0
       0  4642.9    52.9  6093.2       0    53.6
Permanent Ineff=
       F       F
Bank Sta=4977.4,5017.9
XS Rating Curve= 0
Exp/Cntr=.3,.1

Type RM Length L Ch R = 1 ,11742.5 ,605.6,664.6,603
BEGIN DESCRIPTION:
Cross Section 11742.5
END DESCRIPTION:
XS GIS Cut Line= 6
      3152277.71     13883436.85      3151703.61     13882597.58
      3151476.88     13882340.43      3151382.87     13882238.12
      3151081.48     13881969.91      3149586.59     13881062.18
#Sta/Elev= 30
  3574.9    53.3  3684.9    52.5  3699.9      52  3719.9    51.8  4094.9    52.5
  4194.9    50.9  4319.9    51.9  4339.9    51.4  4434.9    51.8  4489.9    51.4
  4591.8    51.4  4626.8    51.1  4691.8    51.3  4731.8    51.1  4826.8    51.7
  4977.4    50.3  4994.2   43.63  4996.3   43.62  4999.5   42.74  5003.4   42.99
  5005.8   43.68  5017.9   50.38  5064.6    51.5    5737    51.4    5897    52.2
    5917    51.9    6207    52.8    6407    52.4    7067    52.4  7225.9    53.5
#Mann= 3 , 1 , 0
  3574.9     .08       0  4977.4     .04       0  5017.9     .14       0
#XS Ineff= 2 , 0
       0  4094.9    52.5    6207       0    52.8
Permanent Ineff=
       F       F
Bank Sta=4977.4,5017.9
XS Rating Curve= 0
Exp/Cntr=.3,.1

Type RM Length L Ch R = 1 ,11077.9 ,339.8,510.6,679.3
BEGIN DESCRIPTION:
Cross Section 11077.9
END DESCRIPTION:
XS GIS Cut Line= 6
      3152669.15     13883575.36      3152367.67     13882526.94
      3152057.54     13882030.74      3151944.17     13881862.08
       3151728.5      13881654.7      3149498.91     13880781.49
#Sta/Elev= 30
  3197.1   53.54  3217.1   52.81  3277.1   53.15  3287.1   52.14  3887.1   51.52
  3967.1   52.21    4288   52.47    4338   52.15    4438   50.22    4618    51.3
    4748   49.91  4873.1   50.43  4913.1   49.76  4965.9    51.6  4979.4   50.87
  4995.8   43.21  4997.5   41.45  5000.6   41.17  5003.5   41.44  5004.1   42.85
  5023.4   50.94  5045.7   50.91  5053.1   50.39  5076.3   50.86  5955.5   51.15
  5985.5   50.76  6125.5   51.43  6885.5   52.11  6905.5   52.83    7770   53.29
#Mann= 4 , 1 , 0
  3197.1     .08       0  4979.4     .04       0  5023.4     .14       0
    7770      .2       0
#XS Ineff= 2 , 0
       0    4288   52.47               0
Permanent Ineff=
       F       F
Bank Sta=4979.4,5023.4
XS Rating Curve= 0
Exp/Cntr=.3,.1

Type RM Length L Ch R = 1 ,10567.3 ,280.7,369.3,553.7
BEGIN DESCRIPTION:
Cross Section 10567.3-Interpolated
END DESCRIPTION:
XS GIS Cut Line= 5
      3152720.96      13883524.3       3152503.1      13881756.9
      3152345.33       13881562.      3151472.92     13880485.42
      3150908.26     13879700.84
#Sta/Elev= 30
  3081.8   53.17  3261.8   52.27  3701.8   51.37  3771.8   52.68  4151.8   52.49
  4181.8   52.22  4201.8   51.24  4381.8   50.97  4591.8   51.31  4621.8   52.24
  4642.4   52.19  4741.8   51.92  4771.8    50.7  4952.5   50.27  4979.4   50.75
  4995.8   43.09  4997.5   41.33  5000.6   41.05  5003.5   41.32  5004.1   42.73
  5023.4   50.82  5052.5   51.05  5062.5   51.68  5082.5   50.99  5323.3    50.7
  5373.3   50.13    5482    50.5  6293.3   51.66    7069    51.4  7465.6   52.44
#Mann= 5 , 1 , 0
  3081.8     .99       0  4642.4     .08       0  4979.4     .04       0
  5023.4     .14       0    5482     .99       0
#XS Ineff= 2 , 0
       0  3771.8   52.68               0
Permanent Ineff=
       F       F
Bank Sta=4979.4,5023.4
XS Rating Curve= 0
Exp/Cntr=.3,.1