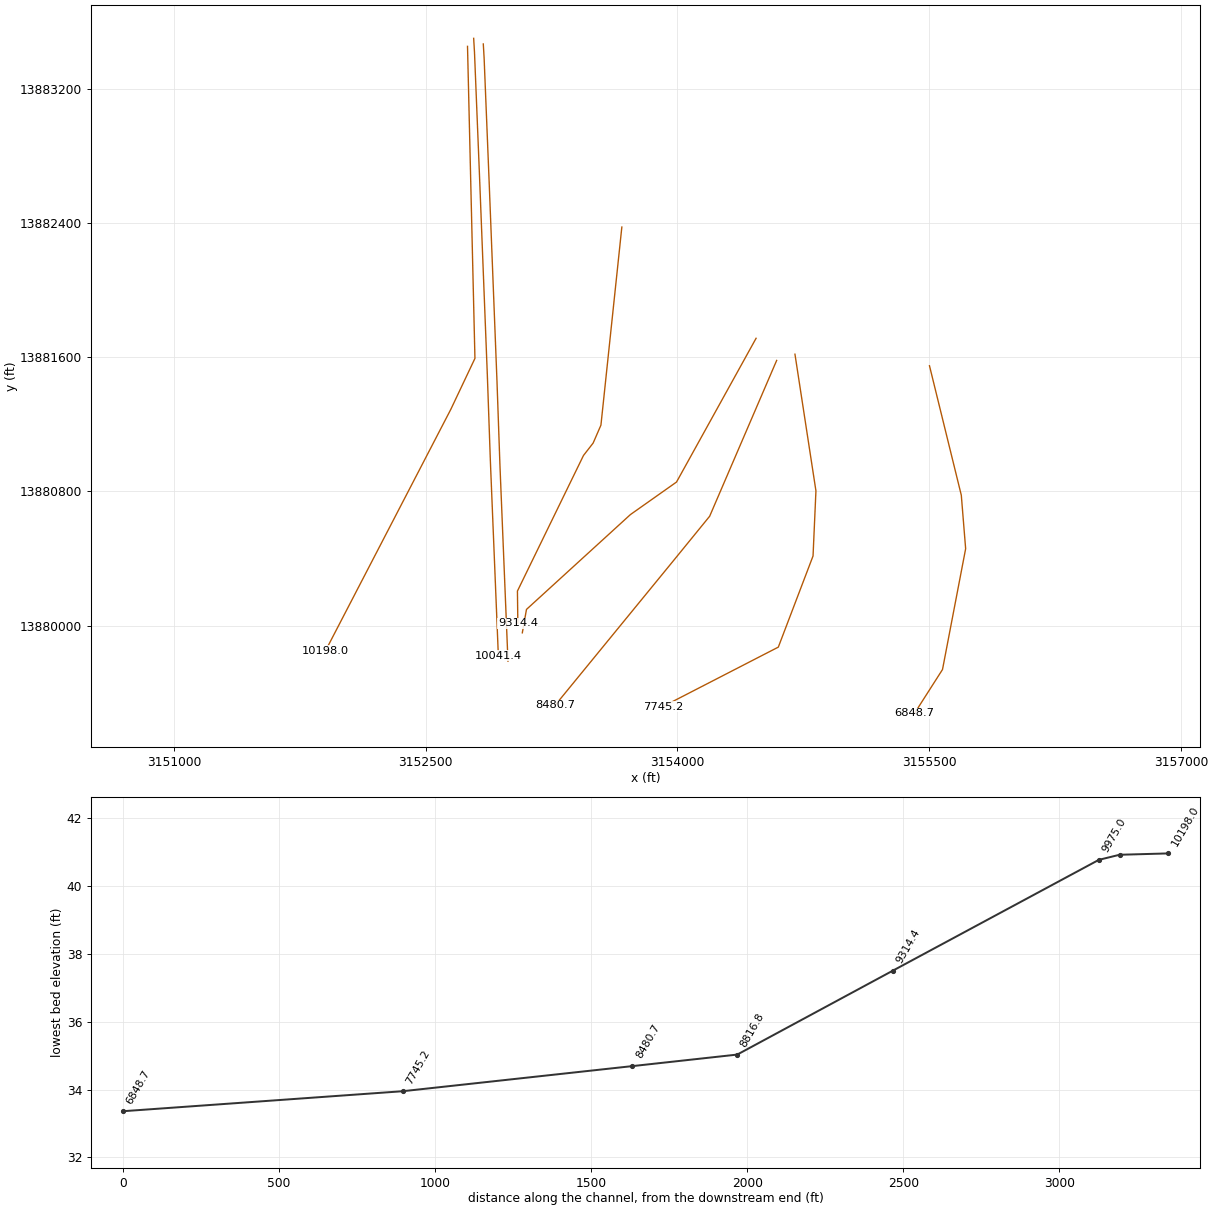
HEC-RAS study P125-00-00.PRJ: P125-00-00

--- P125-00-00.g01 (geometry) --- (continued)

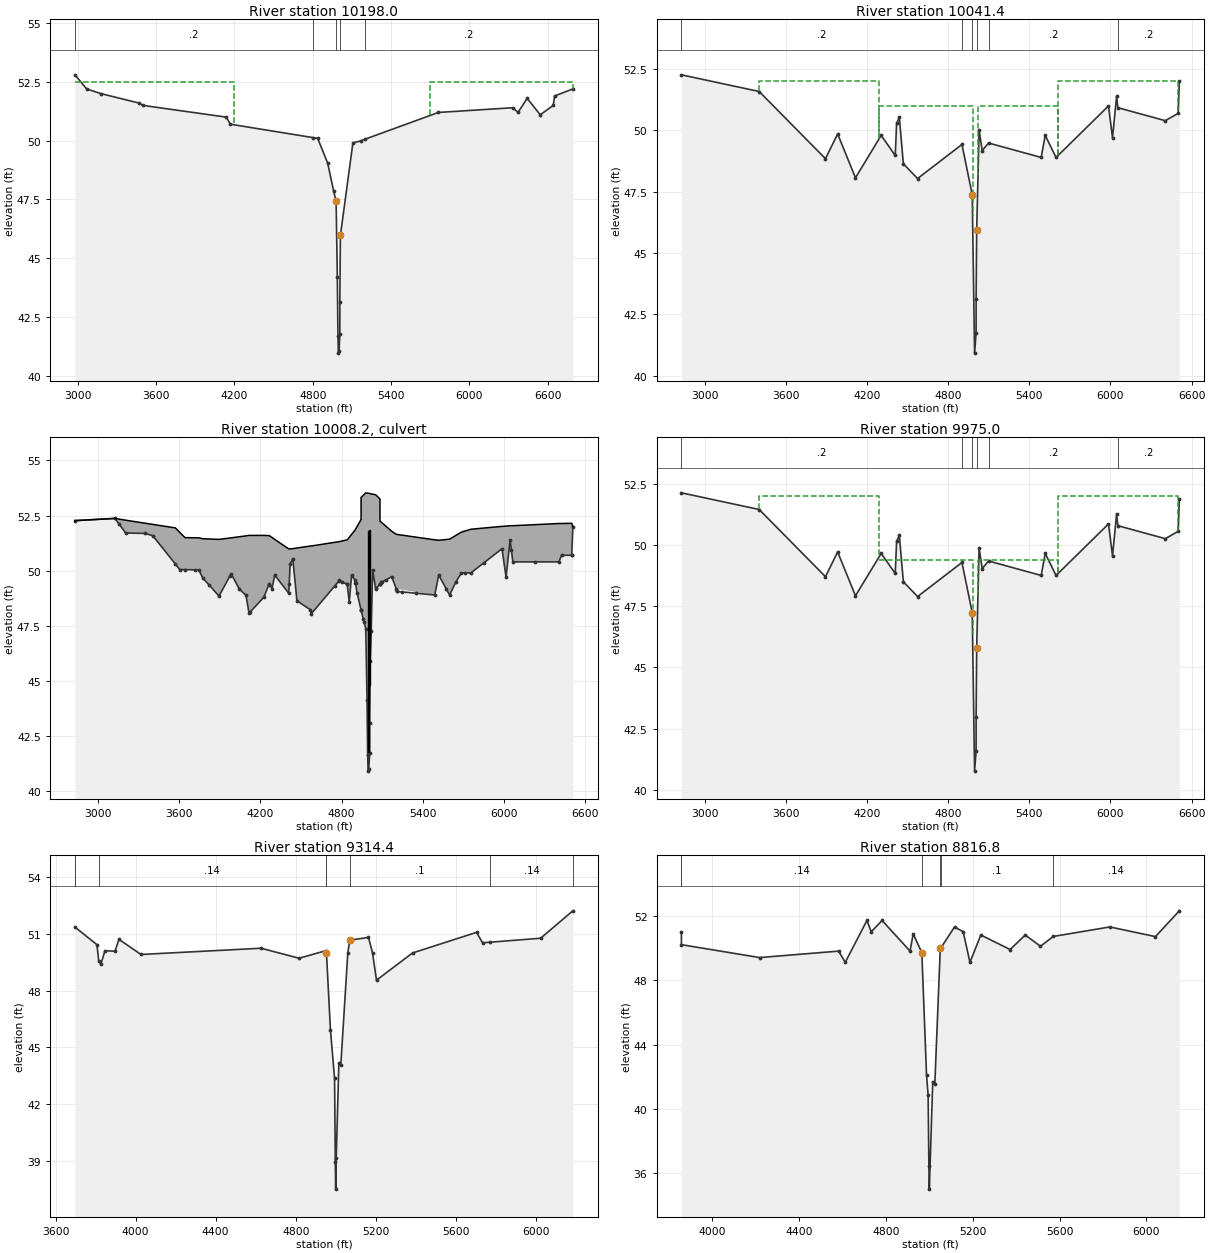
Type RM Length L Ch R = 1 ,10198.0 ,93.8,156.6,407
BEGIN DESCRIPTION:
Cross Section 10198.0-Interpolated
END DESCRIPTION:
XS GIS Cut Line= 4
      3152749.56      13883451.8      3152793.83     13881592.65
      3152650.32      13881289.7      3151904.15     13879851.77
#Sta/Elev= 30
  2977.6    52.8  3067.6    52.2  3177.6      52  3467.6    51.6  3497.6    51.5
  4137.6      51  4167.6    50.7  4800.2   50.13  4837.2    50.1 4914.27   49.04
 4959.82   47.85  4978.7   47.42 4987.96   44.19 4992.73   41.69 4996.02   40.96
 5001.39   41.04 5007.27   41.79 5007.36   43.15  5011.6   45.97  5107.2    49.9
  5172.5      50  5199.6   50.06  5762.5    51.2  6332.5    51.4  6372.5    51.2
  6442.5    51.8  6542.5    51.1  6642.5    51.5  6652.5    51.9  6792.5    52.2
#Mann= 5 , 1 , 0
  2977.6      .2       0  4800.2     .08       0  4978.7     .04       0
  5011.6     .14       0  5199.6      .2       0
#XS Ineff= 2 , 0
       0    4200    52.5    5700       0    52.5
Permanent Ineff=
       F       F
Bank Sta=4978.7,5011.6
XS Rating Curve= 0
Exp/Cntr=.5,.3

Type RM Length L Ch R = 1 ,10041.4 ,66.4,66.4,66.4
BEGIN DESCRIPTION:
Upstream Section of Bridge/Culvert/Weir
END DESCRIPTION:
XS GIS Cut Line= 6
      3152786.24      13883499.5      3152791.11     13883416.79
      3152821.16     13882676.58      3152867.79      13881490.6
      3152885.48     13880988.47      3152933.27     13879822.46
#Sta/Elev= 30
  2829.2   52.27    3404   51.59    3894   48.85    3984   49.86  4115.7   48.07
  4305.7    49.8  4409.7   48.98  4419.7   50.29  4439.7   50.54  4469.7   48.64
  4574.8   48.04  4902.8   49.43  4978.7   47.38 4996.02   40.92 5007.27   41.75
 5007.36   43.11  5011.6   45.93 5029.44   50.02 5052.31   49.18  5099.2   49.49
  5488.2    48.9  5518.2    49.8  5598.2    48.9  5985.6      51  6015.6    49.7
  6045.6    51.4    6055   50.93  6405.6    50.4  6500.9    50.7  6509.2      52
#Mann= 6 , 1 , 0
  2829.2      .2       0  4902.8     .08       0  4978.7    .035       0
  5011.6     .08       0  5099.2      .2       0    6055      .2       0
#XS Ineff= 4 ,-1
    3400  4289.9      52    4290    4981      51    5021  5614.9      51
    5615    6500      52
Permanent Ineff=
       F       F       F       F
Bank Sta=4978.7,5011.6
XS Rating Curve= 0
Exp/Cntr=.5,.3

Type RM Length L Ch R = 2 ,10008.2 ,,,
BEGIN DESCRIPTION:
MESA DRIVE, SKEW ANGLE OF 30 DEGREES
Structure ID: P25-1
END DESCRIPTION:
Bridge Culvert--1,0,-1,-1, 0
Deck Dist Width WeirC Skew NumUp NumDn MinLoCord MaxHiCord MaxSubmerge Is_Ogee
10,46.4,3,0, 60, 60, , , .95, 0, 1,1,,
  2829.2    3124    3204    3404    3572    3604    3642    3744    3774    3894
    3984    4044    4094  4115.7  4225.7  4265.7  4285.7  4305.7  4409.7  4412.9
  4419.7  4439.7  4469.7  4569.7  4574.8 4783.93 4841.61 4856.24 4874.26 4899.28
 4943.99  4944.1  4978.7 4987.96 4992.73 4996.02 5001.39 5007.27 5007.36  5011.6
 5018.88 5029.44 5052.31  5083.6 5083.71 5170.34  5204.1  5488.2  5518.2  5598.2
  5685.6  5755.6  5985.6  6015.6  6045.6  6065.6  6405.6  6425.6  6500.9  6509.2
   52.27   52.37   52.29    52.1   51.94   51.74    51.5   51.49   51.45   51.42
   51.49   51.54   51.58    51.6    51.6   51.59   51.51   51.42   50.99   50.98
   50.99      51   51.03   51.12   51.12   51.32    51.4   51.51   51.65   51.84
   52.32   53.32   53.53   53.52   53.52   53.51   53.51    53.5    53.5   53.49
   53.48   53.47   53.44   53.25   52.25   51.79   51.65    51.4   51.38   51.43
   51.75   51.88   52.01   52.02   52.04   52.04   52.14   52.14   52.15      52
   52.27   52.37   51.71   51.59    50.3   50.05   50.05   50.04   49.67   48.85
   49.86   49.17   48.88   48.07    48.8   49.41   49.19    49.8   48.98    49.4
   50.29   50.54   48.64   48.23   48.04   49.56    49.4   48.58    49.8   49.56
   48.22   48.22   47.38   44.15   41.65   40.92      41   41.75   43.11   45.93
   47.28   50.02   49.18   49.39   49.39   49.73   49.18    48.9    49.8    48.9
    49.9    49.9      51    49.7    51.4    50.4    50.4    50.7    50.7      52
  2829.2    3124    3204    3404    3572    3604    3642    3744    3774    3894
    3984    4044    4094  4115.7  4225.7  4265.7  4285.7  4305.7  4409.7  4412.9
  4419.7  4439.7  4469.7  4569.7  4574.8 4783.93 4841.61 4856.24 4874.26 4899.28
 4943.99  4944.1  4978.7 4987.96 4992.73 4996.02 5001.39 5007.27 5007.36  5011.6
 5018.88 5029.44 5052.31  5083.6 5083.71 5170.34  5204.1  5488.2  5518.2  5598.2
  5685.6  5755.6  5985.6  6015.6  6045.6  6065.6  6405.6  6425.6  6500.9  6509.2
   52.27   52.37   52.29    52.1   51.94   51.74    51.5   51.49   51.45   51.42
   51.49   51.54   51.58    51.6    51.6   51.59   51.51   51.42   50.99   50.98
   50.99      51   51.03   51.12   51.12   51.32    51.4   51.51   51.65   51.84
   52.32   53.32   53.53   53.52   53.52   53.51   53.51    53.5    53.5   53.49
   53.48   53.47   53.44   53.25   52.25   51.79   51.65    51.4   51.38   51.43
   51.75   51.88   52.01   52.02   52.04   52.04   52.14   52.14   52.15      52
   52.17   52.27   51.61   51.49    50.2   49.95   49.95   49.94   49.57   48.75
   49.76   49.07   48.78   47.97    48.7   49.31   49.09    49.7   48.88    49.3
   50.19   50.44   48.54   48.13   47.94   49.46    49.3   48.48    49.7   49.46
   48.12   48.12   47.28   44.05   41.55   40.82    40.9   41.65   43.01   45.83
   47.18   49.92   49.08   49.29   49.29   49.63   49.08    48.8    49.7    48.8
    49.8    49.8    50.9    49.6    51.3    50.3    50.3    50.6    50.6    51.9
BR Coef= 1 , 0 , 0 ,1.25, 0 ,,,.8,-1,2,0,
WSPro=,,,, 1 ,,,, 0 ,,,, 0 ,,,,-1 ,-1 ,-1 , 0 , 0 , 0 , 0 , 0
Culvert=2,10,8.7,46.4,.015,.4,1,8,1,41.78,4995.9,41.68,4995.9,Culvert #1  , 0 ,10
Culvert Bottom n=.015
Culvert=2,7,8.7,46.4,.015,.4,1,8,1,44.84,5006.7,44.74,5006.7,Culvert #2  , 0 ,10
Culvert Bottom n=.015
BR U #Sta/Elev= 93
  2829.2   52.27    3124   52.37    3152   52.14    3204   51.71    3344   51.69
    3404   51.59    3572    50.3    3604   50.05    3642   50.05  3712.9   50.04
    3744   50.04    3774   49.67  3822.9   49.34    3894   48.85  3972.9   49.74
    3984   49.86    4044   49.17    4094   48.88  4115.7   48.07  4122.9   48.12
  4225.7    48.8  4262.9   49.37  4265.7   49.41  4285.7   49.19  4305.7    49.8
  4409.7   48.98  4412.9    49.4  4419.7   50.29  4439.7   50.54  4469.7   48.64
  4569.7   48.23  4574.8   48.04  4748.4    49.3 4783.93   49.56 4784.19   49.54
 4800.21   49.49  4839.7    49.4 4841.61    49.4 4856.24   48.58 4874.26    49.8
 4899.28   49.56  4901.9   49.46  4902.8   49.43 4914.27      49 4943.99   48.22
  4944.1   48.22 4944.21   48.22 4959.82   47.81    4965   47.69  4978.7   47.38
 4987.96   44.15 4992.73   41.65 4996.02   40.92 5001.39      41 5007.27   41.75
 5007.36   43.11  5011.6   45.93 5018.88   47.28 5029.44   50.02 5052.31   49.18
  5055.6    49.2 5083.49   49.39  5083.6   49.39 5083.71   49.39 5094.83   49.47
  5099.2   49.49    5125   49.57 5170.34   49.73  5204.1   49.18  5210.7   49.07
 5210.78   49.06  5244.9   49.04  5352.2   48.98  5488.2    48.9  5518.2    49.8
  5572.2   49.19  5598.2    48.9  5645.6    49.5  5685.6    49.9  5712.2    49.9
  5755.6    49.9  5852.2   50.36  5985.6      51  6015.6    49.7  6045.6    51.4
    6055   50.93  6065.6    50.4  6230.5    50.4  6405.6    50.4  6425.6    50.7
  6500.9    50.7    6501   50.72  6509.2      52
BR U #Mann= 6
  2829.2      .2  4902.8     .08  4978.7    .035  5011.6     .08  5099.2      .2
    6055      .2
BR U Banks=4978.7,5011.6
BR D #Sta/Elev= 93
  2829.2   52.17    3124   52.27    3152   52.04    3204   51.61    3344   51.59
    3404   51.49    3572    50.2    3604   49.95    3642   49.95  3712.9   49.94
    3744   49.94    3774   49.57  3822.9   49.24    3894   48.75  3972.9   49.64
    3984   49.76    4044   49.07    4094   48.78  4115.7   47.97  4122.9   48.02
  4225.7    48.7  4262.9   49.27  4265.7   49.31  4285.7   49.09  4305.7    49.7
  4409.7   48.88  4412.9    49.3  4419.7   50.19  4439.7   50.44  4469.7   48.54
  4569.7   48.13  4574.8   47.94  4748.4    49.2 4783.93   49.46 4784.19   49.44
 4800.21   49.39  4839.7    49.3 4841.61    49.3 4856.24   48.48 4874.26    49.7
 4899.28   49.46  4901.9   49.36  4902.8   49.33 4914.27    48.9 4943.99   48.12
  4944.1   48.12 4944.21   48.12 4959.82   47.71    4965   47.59  4978.7   47.28
 4987.96   44.05 4992.73   41.55 4996.02   40.82 5001.39    40.9 5007.27   41.65
 5007.36   43.01  5011.6   45.83 5018.88   47.18 5029.44   49.92 5052.31   49.08
  5055.6    49.1 5083.49   49.29  5083.6   49.29 5083.71   49.29 5094.83   49.37
  5099.2   49.39    5125   49.47 5170.34   49.63  5204.1   49.08  5210.7   48.97
 5210.78   48.96  5244.9   48.94  5352.2   48.88  5488.2    48.8  5518.2    49.7
  5572.2   49.09  5598.2    48.8  5645.6    49.4  5685.6    49.8  5712.2    49.8
  5755.6    49.8  5852.2   50.26  5985.6    50.9  6015.6    49.6  6045.6    51.3
    6055   50.83  6065.6    50.3  6230.5    50.3  6405.6    50.3  6425.6    50.6
  6500.9    50.6    6501   50.62  6509.2    51.9
BR D #Mann= 6
  2829.2      .2  4902.8     .08  4978.7    .035  5011.6     .08  5099.2      .2
    6055      .2
BR D Banks=4978.7,5011.6
BC Design=,, 0 ,, 0 ,,,,,,

Type RM Length L Ch R = 1 ,9975.0  ,660.6,660.6,660.6
BEGIN DESCRIPTION:
Downstream Section of Bridge/Culvert/Weir
END DESCRIPTION:
XS GIS Cut Line= 6
      3152843.58     13883466.02      3152848.45     13883383.31
       3152878.5      13882643.1      3152925.13     13881457.12
      3152942.82     13880954.99      3152990.62     13879788.98
#Sta/Elev= 30
  2829.2   52.12    3404   51.44    3894    48.7    3984   49.71  4115.7   47.92
  4305.7   49.65  4409.7   48.83  4419.7   50.14  4439.7   50.39  4469.7   48.49
  4574.8   47.89  4902.8   49.28  4978.7   47.23 4996.02   40.77 5007.27    41.6
 5007.36   42.96  5011.6   45.78 5029.44   49.87 5052.31   49.03  5099.2   49.34
  5488.2   48.75  5518.2   49.65  5598.2   48.75  5985.6   50.85  6015.6   49.55
  6045.6   51.25    6055   50.78  6405.6   50.25  6500.9   50.55  6509.2   51.85
#Mann= 6 , 1 , 0
  2829.2      .2       0  4902.8     .08       0  4978.7    .035       0
  5011.6     .08       0  5099.2      .2       0    6055      .2       0
#XS Ineff= 4 ,-1
    3400  4289.9      52    4290    4981    49.4    5021  5614.9    49.4
    5615    6500      52
Permanent Ineff=
       F       F       F       F
Bank Sta=4978.7,5011.6
XS Rating Curve= 0
Exp/Cntr=.5,.3

Type RM Length L Ch R = 1 ,9314.4  ,532.9,497.6,462.1
BEGIN DESCRIPTION:
Cross Section 9314.4-Interpolated
END DESCRIPTION:
XS GIS Cut Line= 6
        3153669.      13882375.2      3153544.44     13881195.17
      3153498.08     13881088.49      3153440.47     13881014.43
      3153046.95     13880206.66      3153049.46     13880014.18
#Sta/Elev= 30
  3696.9   51.37  3806.9   50.44  3815.7   49.59  3826.9   49.42  3846.9   50.12
  3896.9   50.09  3916.9   50.72  4026.9   49.92  4626.9   50.25  4816.9   49.72
  4950.1   50.12  4953.5   50.02  4973.5   45.92  4994.1   43.36  4997.7   38.91
  4999.7    37.5  5002.4   39.15  5015.5   44.17  5025.1   44.05  5060.3   50.01
  5070.3   50.68  5163.6   50.82  5183.6   50.01  5203.6   48.56  5383.6      50
  5703.6   51.09  5733.6   50.54  5772.9   50.57  6023.6   50.78  6184.6   52.23
#Mann= 8 , 1 , 0
  3696.9      .2       0  3696.9      .1       0  3815.7     .14       0
  4950.1      .1       0  4953.5    .035       0  5070.3      .1       0
  5772.9     .14       0  6184.6      .2       0
#XS Ineff= 2 , 0
       0                  5163.6       0   50.82
Permanent Ineff=
       F       F
Bank Sta=4953.5,5070.3
XS Rating Curve= 0
Exp/Cntr=.3,.1

Type RM Length L Ch R = 1 ,8816.8  ,317.6,336.1,359.7
BEGIN DESCRIPTION:
Cross Section 8816.8
END DESCRIPTION:
XS GIS Cut Line= 6
      3154468.73     13881712.57      3153994.78     13880856.22
       3153720.1     13880662.33      3153158.35     13880149.77
      3153100.84      13880097.3      3153076.05      13879957.8
#Sta/Elev= 30
  3856.9      51    3857    50.2    4217    49.4    4582    49.8    4612    49.1
    4712    51.7    4732      51    4782    51.7  4910.8    49.8  4925.3   50.87
  4965.1   49.71  4986.9   42.09  4994.1   40.89  4997.7   36.44  4999.7   35.03
  5015.5    41.7  5025.1   41.58  5050.4   50.02  5053.1      50  5115.8    51.3
  5155.8      51    5187    49.1    5237    50.8    5372    49.9    5442    50.8
    5512    50.1  5571.1   50.71    5832    51.3    6042    50.7    6152    52.3
#Mann= 6 , 1 , 0
  3856.9      .2       0    3857     .14       0  4965.1     .04       0
  5050.4     .14       0  5053.1      .1       0  5571.1     .14       0
#XS Ineff= 2 , 0
       0  4925.3   50.87  5115.8       0    51.3
Permanent Ineff=
       F       F
Bank Sta=4965.1,5050.4
XS Rating Curve= 0
Exp/Cntr=.3,.1

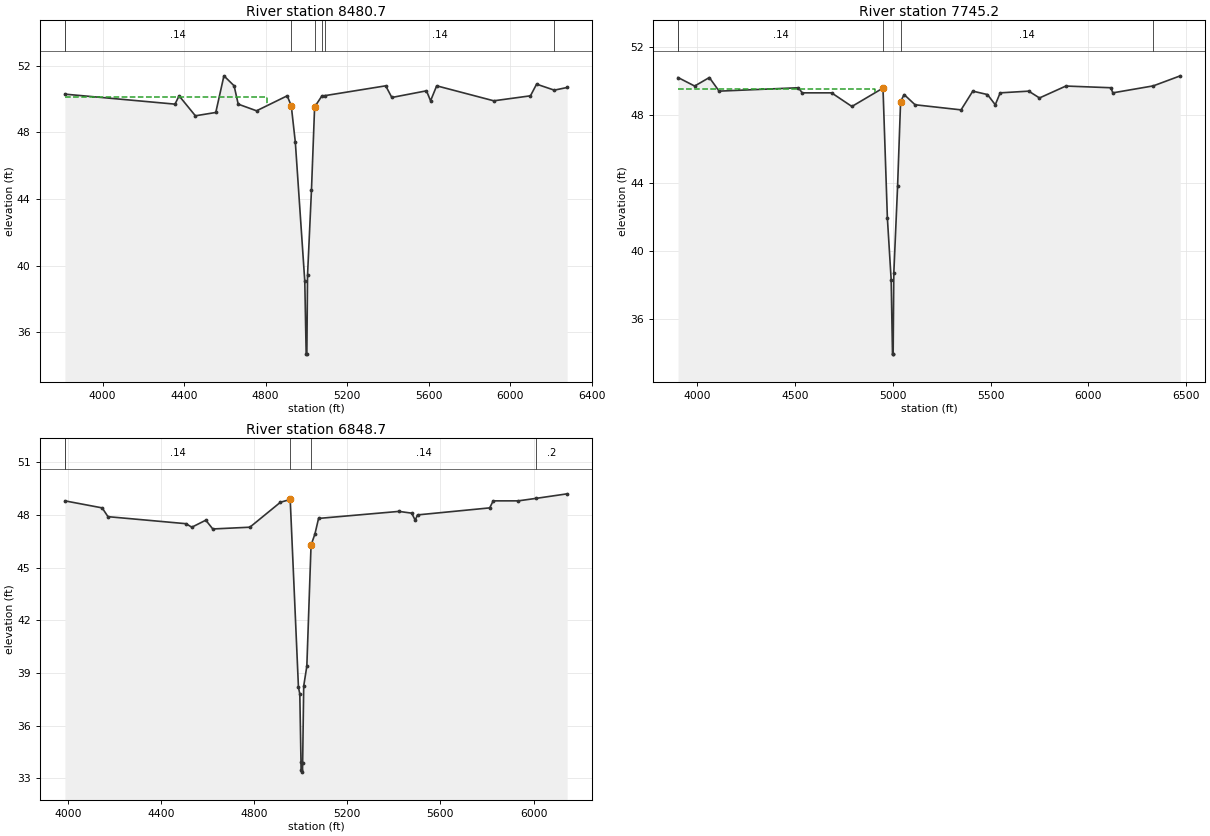
Type RM Length L Ch R = 1 ,8480.7  ,698.7,735.5,756.7
BEGIN DESCRIPTION:
Cross Section 8480.7-Interpolated
END DESCRIPTION:
XS GIS Cut Line= 4
       3154591.3     13881580.57      3154192.23     13880652.48
      3153988.05     13880401.89      3153272.51     13879527.35
#Sta/Elev= 30
  3815.3    50.3  4355.3    49.7  4375.3    50.2  4455.3      49  4555.3    49.2
  4595.3    51.4  4645.3    50.8  4665.3    49.7  4755.3    49.3  4905.6    50.2
  4925.6    49.6  4945.6    47.4  4991.9   39.06  4998.7   34.69    5002   34.69
  5005.4   39.44  5024.7   44.55  5040.1   49.53  5076.2    50.2  5090.5   50.21
  5388.8    50.8  5418.8    50.1  5588.8    50.5  5608.8    49.9  5638.8    50.8
  5918.8    49.9  6098.8    50.2  6128.8    50.9  6215.6   50.54  6278.8    50.7
#Mann= 7 , 1 , 0
  3815.3      .2       0  3815.3     .14       0  4925.6     .04       0
  5040.1     .14       0  5076.2      .1       0  5090.5     .14       0
  6215.6      .2       0
#XS Ineff= 2 , 0
       0  4805.3    50.1               0
Permanent Ineff=
       F       F
Bank Sta=4925.6,5040.1
XS Rating Curve= 0
Exp/Cntr=.3,.1

Type RM Length L Ch R = 1 ,7745.2  ,891.3,896.5,904.2
BEGIN DESCRIPTION:
Cross Section 7745.2
END DESCRIPTION:
XS GIS Cut Line= 5
      3154700.32     13881617.78      3154825.28     13880803.44
      3154808.04     13880415.66      3154601.23     13879872.77
      3153912.21     13879517.94
#Sta/Elev= 30
  3902.2    50.2  3987.2    49.7  4062.2    50.2  4112.2    49.4  4517.2    49.6
  4537.2    49.3  4687.2    49.3  4791.1    48.5  4950.1   49.58  4972.6   41.93
  4991.9   38.32  4998.7   33.95    5002   33.95  5005.4    38.7  5024.7   43.81
  5040.1   48.79  5058.1    49.2  5114.2    48.6  5349.2    48.3  5409.2    49.4
  5484.2    49.2  5524.2    48.6  5549.2    49.3  5695.2    49.4  5750.2      49
  5885.2    49.7  6115.2    49.6  6125.2    49.3  6332.2   49.71  6470.2    50.3
#Mann= 5 , 1 , 0
  3902.2      .2       0  3902.2     .14       0  4950.1     .04       0
  5040.1     .14       0  6332.2      .2       0
#XS Ineff= 2 , 0
       0  4911.1    49.5  5409.2       0    49.4
Permanent Ineff=
       F       F
Bank Sta=4950.1,5040.1
XS Rating Curve= 0
Exp/Cntr=.3,.1

Type RM Length L Ch R = 1 ,6848.7  ,1120.4,1162.8,1200.1
BEGIN DESCRIPTION:
Cross Section 6848.7
END DESCRIPTION:
XS GIS Cut Line= 5
      3155501.74     13881548.84      3155691.32     13880777.59
      3155717.17     13880458.75      3155579.29      13879739.2
       3155412.4     13879477.98
#Sta/Elev= 30
  3987.8    48.8  4147.8    48.4  4172.8    47.9  4507.8    47.5  4532.8    47.3
  4592.8    47.7  4622.8    47.2    4782    47.3 4913.25   48.72 4955.25   48.88
 4990.65   38.19 4996.45   37.81 5001.55   33.95 5001.95   33.46 5007.95   33.36
 5008.65    33.9 5013.25   38.26 5026.65   39.39 5044.75   46.28 5061.35   46.91
    5077    47.8  5421.9    48.2  5476.9    48.1  5491.9    47.7  5501.9      48
  5811.9    48.4  5826.9    48.8  5934.5    48.8  6010.3   48.94  6144.5    49.2
#Mann= 5 , 1 , 0
  3987.8      .2       0  3987.8     .14       0 4955.25     .04       0
 5044.75     .14       0  6010.3      .2       0
#XS Ineff= 2 , 0
       0                  5421.9       0    48.2
Permanent Ineff=
       F       F
Bank Sta=4955.25,5044.75
XS Rating Curve= 0
Exp/Cntr=.3,.1