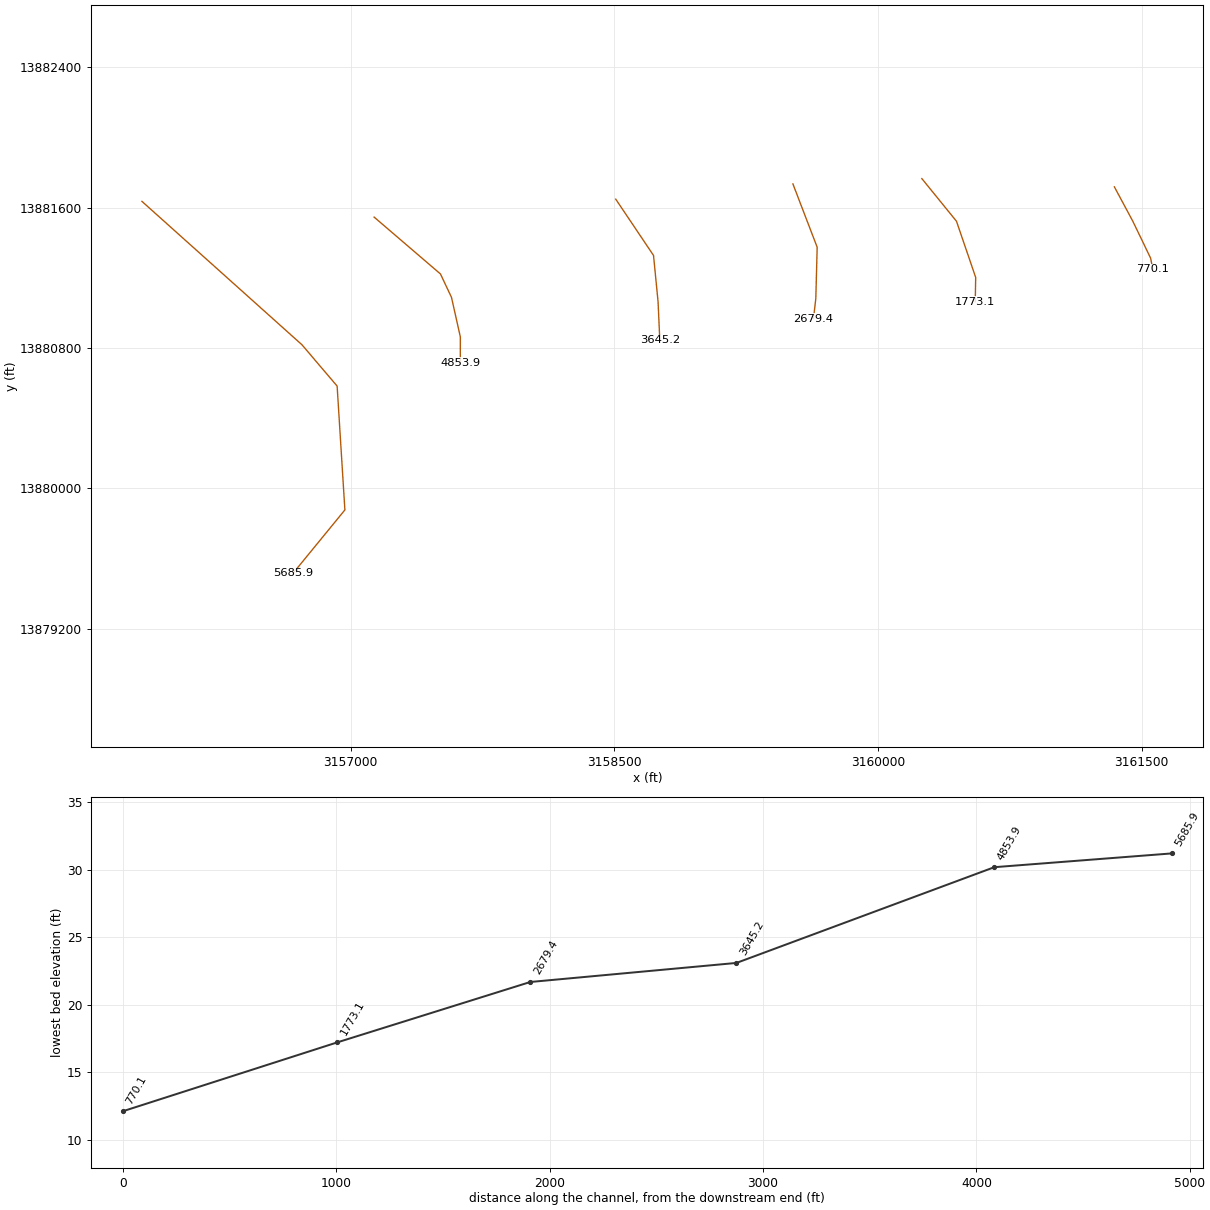
HEC-RAS study P125-00-00.PRJ: P125-00-00

--- P125-00-00.g01 (geometry) --- (continued)

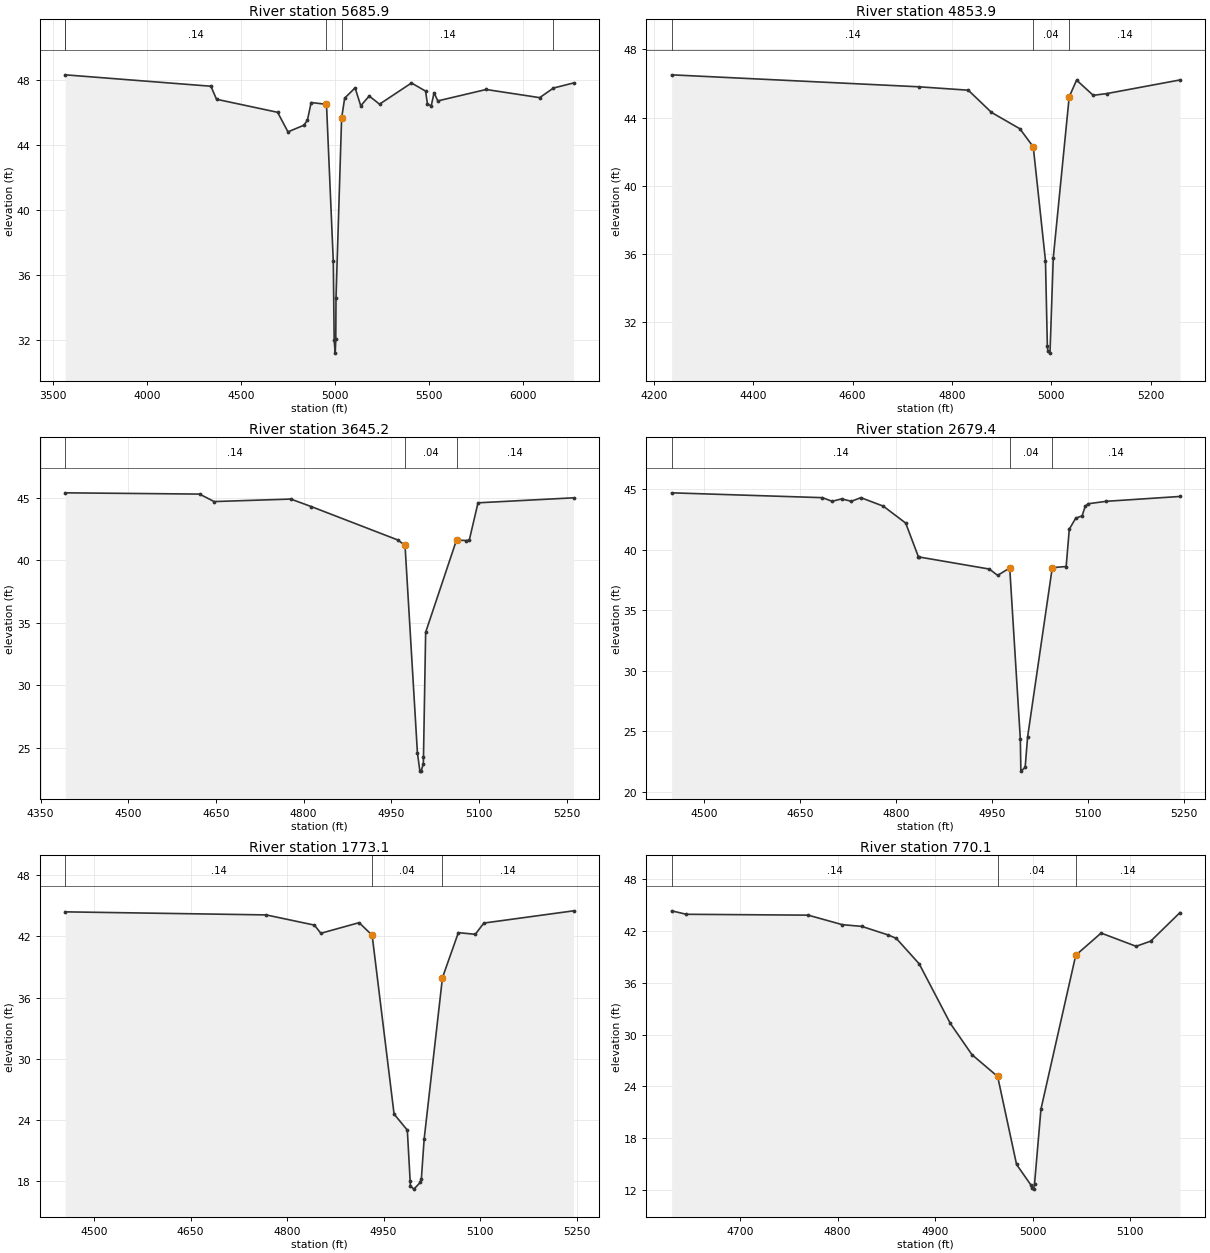
Type RM Length L Ch R = 1 ,5685.9  ,863.9,832,807.5
BEGIN DESCRIPTION:
Cross Section 5685.9
END DESCRIPTION:
XS GIS Cut Line= 5
      3155811.96     13881635.01      3156722.49     13880818.04
      3156922.54     13880582.76      3156966.68     13879877.08
      3156672.34     13879517.13
#Sta/Elev= 30
  3564.9    48.3  4339.9    47.6  4369.9    46.8  4694.9      46  4749.9    44.8
  4833.2    45.2  4853.2    45.5  4873.2    46.6  4954.9   46.49  4991.1   36.85
  4995.8      32  5001.2   31.22  5004.3   32.07  5005.5   34.61  5035.3   45.64
  5051.6   46.87  5107.1    47.5  5137.1    46.4  5182.1      47  5237.1    46.5
  5407.1    47.8  5482.1    47.3  5492.1    46.5  5512.1    46.4  5527.1    47.2
  5547.1    46.7  5804.1    47.4  6089.1    46.9  6162.4   47.49  6269.1    47.8
#Mann= 5 , 1 , 0
  3564.9      .2       0  3564.9     .14       0  4954.9     .04       0
  5035.3     .14       0  6162.4      .2       0
Bank Sta=4954.9,5035.3
XS Rating Curve= 0
Exp/Cntr=.3,.1

Type RM Length L Ch R = 1 ,4853.9  ,1162,1208.7,1147.9
BEGIN DESCRIPTION:
Cross Section 4853.9
END DESCRIPTION:
XS GIS Cut Line= 5
      3157133.12     13881545.42      3157510.61     13881221.41
      3157573.08     13881088.66      3157623.84      13880862.2
      3157623.18     13880714.47
#Sta/Elev= 16
  4235.4    46.5  4732.9    45.8  4832.9    45.6  4879.6    44.3  4936.9   43.34
  4963.8   42.28  4988.4   35.62  4992.2   30.61  4993.2   30.33  4997.5    30.2
  5004.1   35.78  5036.2   45.21  5051.1   46.19  5084.6    45.3  5111.6    45.4
  5259.4    46.2
#Mann= 3 , 1 , 0
  4235.4     .14       0  4963.8     .04       0  5036.2     .14       0
Bank Sta=4963.8,5036.2
XS Rating Curve= 0
Exp/Cntr=.3,.1

Type RM Length L Ch R = 1 ,3645.2  ,923.3,965.8,914.7
BEGIN DESCRIPTION:
Cross Section 3645.2
END DESCRIPTION:
XS GIS Cut Line= 4
       3158507.8      13881647.8      3158722.88     13881327.13
      3158748.77     13881063.05      3158758.55     13880844.73
#Sta/Elev= 18
    4392    45.4  4621.9    45.3  4646.9    44.7  4778.1    44.9  4813.1    44.3
  4960.9   41.63  4973.6    41.2  4994.8   24.59    4999   23.12  5001.1   23.11
  5004.9   23.69  5005.2   24.26  5008.9   34.23  5061.7   41.62  5077.5   41.58
  5083.5    41.6  5098.5    44.6    5262      45
#Mann= 3 , 1 , 0
    4392     .14       0  4973.6     .04       0  5061.7     .14       0
Bank Sta=4973.6,5061.7
XS Rating Curve= 0
Exp/Cntr=.3,.1

Type RM Length L Ch R = 1 ,2679.4  ,873.8,906.3,898.5
BEGIN DESCRIPTION:
Cross Section 2679.4
END DESCRIPTION:
XS GIS Cut Line= 4
      3159516.04     13881734.59      3159654.13     13881373.68
      3159646.32     13881080.85      3159632.85      13880966.6
#Sta/Elev= 26
  4449.5    44.7  4685.2    44.3  4700.2      44  4715.2    44.2  4730.2      44
  4745.2    44.3  4780.2    43.6  4815.2    42.2  4835.2    39.4  4835.9    39.4
  4945.9    38.4  4958.9   37.88  4977.8   38.49  4994.4   24.32  4995.2    21.7
  5001.9      22  5005.7   24.51  5044.3   38.52    5066   38.61  5070.9    41.7
  5080.9    42.6  5090.9    42.8  5095.9    43.6  5100.9    43.8  5128.9      44
  5243.9    44.4
#Mann= 3 , 1 , 0
  4449.5     .14       0  4977.8     .04       0  5044.3     .14       0
Bank Sta=4977.8,5044.3
XS Rating Curve= 0
Exp/Cntr=.3,.1

Type RM Length L Ch R = 1 ,1773.1  ,998.7,1003,1011.1
BEGIN DESCRIPTION:
Cross Section 1773.1
END DESCRIPTION:
XS GIS Cut Line= 4
       3160249.7     13881764.88      3160446.73     13881522.05
      3160556.05     13881201.88      3160553.63     13881062.54
#Sta/Elev= 19
  4455.2    44.4  4767.5    44.1  4842.5    43.1  4852.5    42.3    4912   43.34
  4932.2   42.11  4966.3   24.58  4986.9      23  4991.3   18.01  4991.7   17.53
  4997.1   17.22  5006.9   17.87  5008.7   18.21    5013    22.1  5041.5   37.95
  5066.2   42.36  5092.5    42.2  5105.8    43.3  5245.2    44.5
#Mann= 3 , 1 , 0
  4455.2     .14       0  4932.2     .04       0  5041.5     .14       0
Bank Sta=4932.2,5041.5
XS Rating Curve= 0
Exp/Cntr=.3,.1

Type RM Length L Ch R = 1 ,770.1   ,0,0,0
BEGIN DESCRIPTION:
Cross Section 770.1
END DESCRIPTION:
XS GIS Cut Line= 4
      3161345.13     13881717.97      3161450.16     13881522.05
      3161551.68     13881311.21      3161563.82     13881247.36
#Sta/Elev= 22
  4629.9    44.3  4644.9    43.9  4769.9    43.8  4804.9    42.7  4824.9    42.5
  4852.2    41.5  4860.2   41.12  4883.7   38.18  4915.7   31.28  4937.8   27.68
  4964.2   25.15  4983.6   14.98  4998.1   12.64  4999.4   12.21    5001   12.13
    5002    12.7  5008.6   21.37  5044.3   39.17  5070.3   41.73  5106.2    40.2
  5121.2    40.8  5151.2    44.1
#Mann= 3 , 1 , 0
  4629.9     .14       0  4964.2     .04       0  5044.3     .14       0
Bank Sta=4964.2,5044.3
XS Rating Curve= 0
Exp/Cntr=.3,.1

Chan Stop Cuts=-1